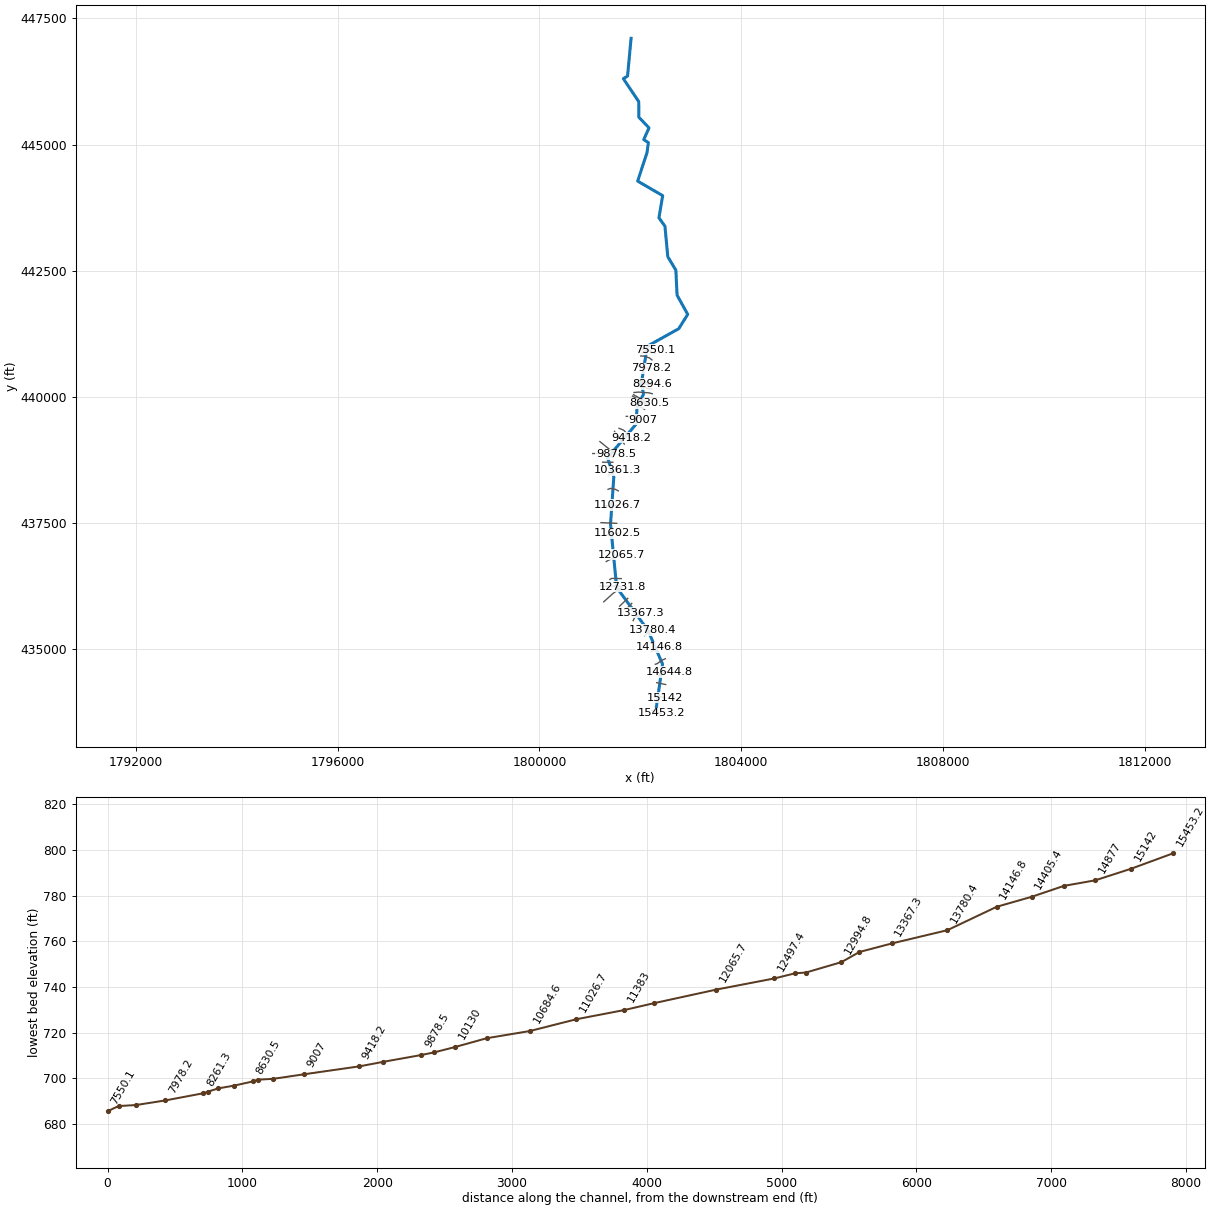
--- LEFTFORK2.prj (project) ---

Proj Title=LEFTFORK2
Current Plan=p01
Default Exp/Contr=0,0
English Units
Geom File=g01
Flow File=f01
Plan File=p01
BEGIN DESCRIPTION:
END DESCRIPTION:
DSS Export Rating Curves= 0
DSS Export Rating Curve Sorted= 0
DSS Export Volume Flow Curves= 0
DXF OffsetX= 0
DXF OffsetY= 0
DXF ScaleX= 0
DXF ScaleY= 0

--- LEFTFORK2.p01 (plan) ---

Plan Title=Floodplain
Program Version=4.00
Geom File=g01
Flow File=f01
K Sum by GR=0
Std Step Tol=0.01
Critical Tol=0.01
Num of Std Step Trials=20
Max Error Tol=0.3
Flow Tol Ratio=0.001
Split Flow NTrial=30
Split Flow Tol=0.02
Split Flow Ratio=0.02
Log Output Level=0
Friction Slope Method=1
Unsteady Friction Slope Method=2
Unsteady Bridges Friction Slope Method=1
Global Log Level=0
CheckData=False
Run HTab=0
Run UNet=0
Run PostProcess=0
UNET Theta=0
UNET Theta Warmup=0
UNET ZTol=0
UNET ZSATol=0
UNET MxIter=0
UNET MaxInSteps=0
UNET DtIC=0
UNET DtMin=0
UNET MaxCRTS=0
UNET WFStab=0
UNET SFStab=0
UNET WFX=0
UNET SFX=0
UNET DSS MLevel=0
UNET DZMax Abort=0
UNET Convert EG Bridges=0
UNET Use Existing IB Tables=0
UNET Froude Limit=0
UNET Froude Power=0
Write IC File=0
Echo Input=False
Echo Output=False
Write Detailed=0

--- LEFTFORK2.f01 (steady flow) ---

Flow Title=NFF Regression Equation
Program Version=4.10
Number of Profiles= 1
Profile Names=P100yr
River Rch & RM=LEFTFORK2,Main            ,15453.2
889.3591
River Rch & RM=LEFTFORK2,Main            ,12649.3
1429.816
River Rch & RM=LEFTFORK2,Main            ,9593.4
1687.856
River Rch & RM=LEFTFORK2,Main            ,7760.6
1773.054
River Rch & RM=LEFTFORK2,Main            ,6319
1923.077
River Rch & RM=LEFTFORK2,Main            ,319
 2114.83
Boundary for River Rch & Prof#=LEFTFORK2,Main            , 1
Up Type= 0
Dn Type= 3
Dn Slope=0.007
DSS Import GetInterval= 0
DSS Import GetPeak= 0
DSS Import FillOption= 0

--- LEFTFORK2.g01 (geometry) ---

Geom Title=USGS 10m DEM
Program Version=4.10

River Reach=LEFTFORK2       ,Main
Reach XY= 30
     1802301.357      433749.721       1802439.2      434710.475
     1802147.316      435385.388     1801529.912      436228.487
     1801408.279      437479.706     1801473.488      438417.072
     1801348.705      438795.761     1801914.026      439461.994
     1801934.643      439798.365     1802062.681      440060.952
     1802020.363      440271.456     1802137.551      441006.048
      1802761.52      441354.327     1802938.332      441637.558
     1802727.829      442016.247     1802702.872      442514.294
     1802543.367      442780.136     1802486.943      443383.435
     1802367.586      443550.535     1802442.455      443988.903
     1801946.579      444276.447     1802133.211      444848.278
     1802158.167      445039.251     1802067.021      445100.015
      1802171.28      445330.765     1801969.365      445542.723
     1801967.526       445851.47     1801663.511      446305.874
     1801745.841       446357.61     1801815.519      447104.719

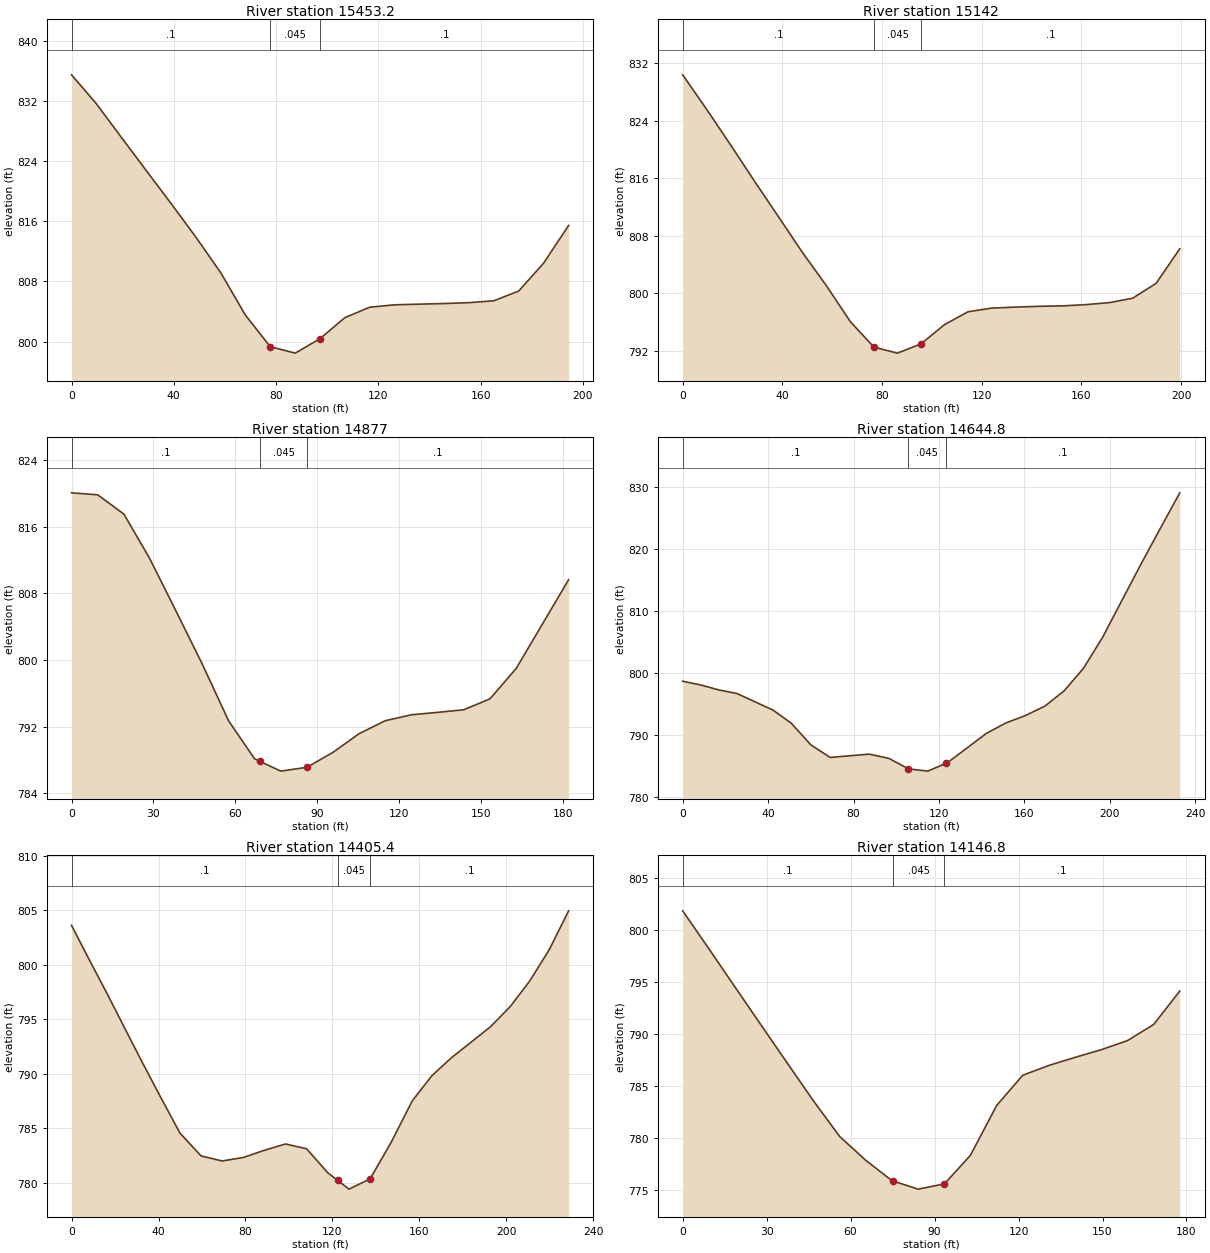
Type RM Length L Ch R = 1 ,15453.2 ,310.1,311.2,312.4
XS GIS Cut Line= 2
     1802226.526        433788.6     1802413.158      433734.346
#Sta/Elev= 23
       0  835.55     9.7   831.7    19.4  827.26    29.2   822.8    38.9  818.41
    48.6  813.93    58.3   809.2      68  803.52    73.4  801.18    77.7  799.31
    87.5  798.45    88.4  798.63    97.2  800.38   106.9  803.18   116.6  804.57
   126.3  804.89     136  804.98   145.8  805.06   155.5  805.18   165.2  805.43
   174.9  806.73   184.6  810.43   194.4  815.47
#Mann= 3 , 0 , 0
       0      .1       0    77.7    .045       0    97.2      .1       0
Bank Sta=77.7,97.2
XS Rating Curve= 0 ,0
Exp/Cntr=0.3,0.1

Type RM Length L Ch R = 1 ,15142   ,264.4,265,265.4
XS GIS Cut Line= 3
     1802294.886      434067.462     1802352.395      434073.973
     1802490.198      434041.421
#Sta/Elev= 24
       0   830.4     9.6  825.61    19.3  820.62    28.9  815.57    38.6  810.59
    48.2  805.63    57.9  800.97    67.3  796.07    76.8  792.52    78.9  792.34
    86.2   791.7    93.9  792.74    95.6  792.97   105.1  795.67   114.5  797.45
     124  797.96   133.4   798.1   142.8  798.21   152.3  798.27   161.7  798.44
   171.2  798.72   180.6  799.34     190   801.4   199.5  806.21
#Mann= 3 , 0 , 0
       0      .1       0    76.8    .045       0    95.6      .1       0
Bank Sta=76.8,95.6
XS Rating Curve= 0 ,0
Exp/Cntr=0.3,0.1

Type RM Length L Ch R = 1 ,14877   ,220,232.2,244.1
XS GIS Cut Line= 2
     1802323.098       434343.07     1802501.049      434305.093
#Sta/Elev= 22
       0  820.09     9.6  819.85    19.2  817.53    28.7  812.15    38.3  805.86
    47.9   799.5    57.5  792.71      67  788.15    69.1  787.82    76.6  786.66
    84.1  787.02    86.2  787.12    95.8  788.93   105.3  791.16   114.9  792.72
   124.5  793.43   134.1  793.72   143.6  794.03   153.2  795.34   162.8  798.99
   172.4  804.32     182  809.65
#Mann= 3 , 0 , 0
       0      .1       0    69.1    .045       0    86.2      .1       0
Bank Sta=69.1,86.2
XS Rating Curve= 0 ,0
Exp/Cntr=0.3,0.1

Type RM Length L Ch R = 1 ,14644.8 ,232.5,239.4,246.3
XS GIS Cut Line= 4
       1802366.5      434479.789     1802394.712      434522.107
     1802490.198      434553.574     1802571.579      434553.574
#Sta/Elev= 29
       0  798.71     8.5   798.1      17   797.3    25.4  796.73    33.9  795.39
    42.4  794.04    50.9  791.93      60  788.46    69.1  786.42    78.3   786.7
    87.4  786.96    96.6  786.27   105.7  784.59   108.1  784.49   114.8  784.22
   123.1  785.45     124  785.58   133.1  787.93   142.3  790.32   151.4  791.99
   160.4  793.16   169.5  794.67   178.5  797.11   187.6  800.74   196.6  805.75
   205.6  811.66   214.7  817.62   223.7  823.34   232.8  829.07
#Mann= 3 , 0 , 0
       0      .1       0   105.7    .045       0   123.1      .1       0
Bank Sta=105.7,123.1
XS Rating Curve= 0 ,0
Exp/Cntr=0.3,0.1

Type RM Length L Ch R = 1 ,14405.4 ,261.8,258.6,255.3
XS GIS Cut Line= 4
     1802295.971      434706.568     1802333.948      434719.589
     1802428.349      434787.949     1802494.539       434816.16
#Sta/Elev= 28
       0  803.62       8  800.53    16.1  797.46    24.1  794.34    32.1  791.23
    40.2  788.16    49.9  784.57    59.6  782.48    69.3  782.02      79  782.34
    88.7     783    98.4  783.58   108.1  783.14   117.8  780.95   122.4  780.24
   127.6  779.44   137.3  780.38   137.4  780.41     147  783.73   156.7  787.53
   165.7  789.83   174.7  791.48   183.7   792.9   192.7  794.33   201.7  796.16
   210.7  798.51   219.7  801.39   228.6  804.95
#Mann= 3 , 0 , 0
       0      .1       0   122.4    .045       0   137.4      .1       0
Bank Sta=122.4,137.4
XS Rating Curve= 0 ,0
Exp/Cntr=0.3,0.1

Type RM Length L Ch R = 1 ,14146.8 ,364.9,366.4,368.5
XS GIS Cut Line= 2
     1802214.591       434959.39     1802371.926      435041.855
#Sta/Elev= 22
       0  801.84     9.4  798.18    18.7  794.51      28  790.86    37.4  787.19
    46.8  783.54    56.1  780.14    65.4  777.85    74.8  775.89    75.3  775.85
    84.1  775.08    90.3  775.41    93.5  775.58   102.8  778.33   112.2  783.13
   121.5  786.03   130.9  786.98   140.2  787.75   149.6  788.49   158.9  789.36
   168.3  790.92   177.6  794.13
#Mann= 3 , 0 , 0
       0      .1       0    75.3    .045       0    93.5      .1       0
Bank Sta=75.3,93.5
XS Rating Curve= 0 ,0
Exp/Cntr=0.3,0.1

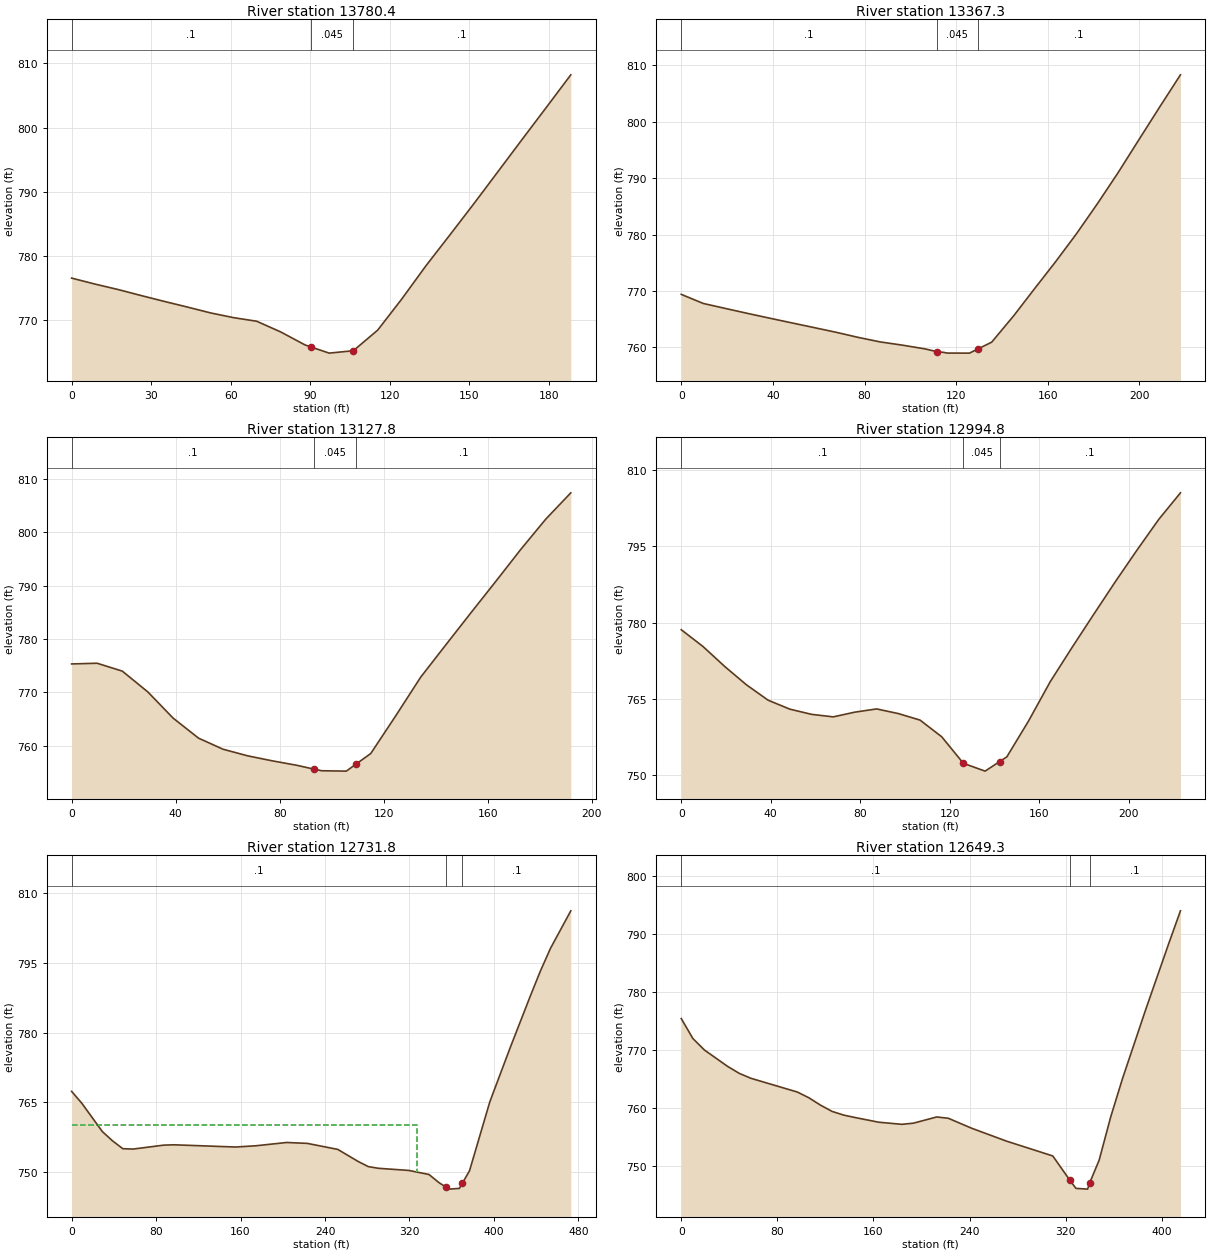
Type RM Length L Ch R = 1 ,13780.4 ,407.3,413.1,418.4
XS GIS Cut Line= 3
     1802084.382      435272.975     1802133.211      435322.888
     1802234.122      435384.737
#Sta/Elev= 24
       0  776.52     8.7   775.6    17.5  774.74    26.2   773.8    34.9  772.89
    43.6  772.01    52.4  771.09    61.1  770.35    69.8  769.79    78.9  768.11
      88   766.1    90.1   765.8    97.1  764.82   105.1  765.15   106.2  765.19
   115.4  768.41   124.4  773.22   133.6  778.45   142.7   783.3   151.8   788.2
   160.9  793.21     170  798.23   179.1  803.21   188.2  808.22
#Mann= 3 , 0 , 0
       0      .1       0    90.1    .045       0   106.2      .1       0
Bank Sta=90.1,106.2
XS Rating Curve= 0 ,0
Exp/Cntr=0.3,0.1

Type RM Length L Ch R = 1 ,13367.3 ,241.8,239.5,238.2
XS GIS Cut Line= 4
     1801856.518      435571.369     1801881.474      435623.452
     1801942.238      435686.386     1801999.747      435730.874
#Sta/Elev= 27
       0  769.41     9.6   767.8    19.2  766.92    28.9  766.04    38.5   765.2
    48.1  764.37    57.8  763.54    67.5   762.7    77.2  761.79    86.9  760.98
    96.6  760.41   106.4  759.75   111.6  759.26   114.4  759.14   116.1  759.01
   125.8     759   129.4  759.72   135.5  760.94   145.2  765.66   154.3  770.46
   163.4  775.19   172.5  780.14   181.6  785.44   190.7  790.98   199.8  796.83
   208.8  802.58   217.9   808.3
#Mann= 3 , 0 , 0
       0      .1       0   111.6    .045       0   129.4      .1       0
Bank Sta=111.6,129.4
XS Rating Curve= 0 ,0
Exp/Cntr=0.3,0.1

Type RM Length L Ch R = 1 ,13127.8 ,131.3,133,133.1
XS GIS Cut Line= 4
     1801681.822      435795.978     1801727.395      435813.339
     1801778.393      435855.657     1801829.391      435913.166
#Sta/Elev= 24
       0  775.33     9.8  775.46    19.5  773.98    29.3  770.09      39   765.2
    48.8  761.44    58.2  759.37    67.7  758.13    77.2  757.19    86.6  756.36
      93  755.66    94.5  755.51    96.1  755.34   105.6  755.27   109.5  756.64
     115  758.57   124.6  765.62   134.2  772.86   143.9  778.93   153.5   784.9
   163.1   790.8   172.7  796.78   182.3  802.44   191.9  807.35
#Mann= 3 , 0 , 0
       0      .1       0      93    .045       0   109.5      .1       0
Bank Sta=93,109.5
XS Rating Curve= 0 ,0
Exp/Cntr=0.3,0.1

Type RM Length L Ch R = 1 ,12994.8 ,266.6,263,260.1
XS GIS Cut Line= 2
     1801589.244      435858.478     1801750.181      436012.992
#Sta/Elev= 26
       0  778.62     9.7  775.33    19.4  771.41    29.1  767.81    38.8  764.78
    48.5  763.02    58.2     762    67.9   761.5    77.6  762.43    87.3  763.06
      97  762.15   106.7  760.87   116.4  757.59   126.1  752.37   127.3  752.18
   135.8  750.84   142.3  752.72   145.5  753.64   155.2  760.68   164.9  768.41
   174.6   775.1   184.3  781.62     194  788.06   203.7  794.28   213.4   800.3
   223.1  805.52
#Mann= 3 , 0 , 0
       0      .1       0   126.1    .045       0   142.3      .1       0
Bank Sta=126.1,142.3
XS Rating Curve= 0 ,0
Exp/Cntr=0.3,0.1

Type RM Length L Ch R = 1 ,12731.8 ,96.3,82.5,68
XS GIS Cut Line= 3
     1801273.488      435943.114     1801452.872      436106.308
     1801640.589      436239.771
#Sta/Elev= 30
       0  767.35     9.7  764.78    29.1  758.69    38.8  756.68    48.5     755
    58.2  754.92    87.3  755.77      97  755.84   155.2  755.36   174.6  755.63
   203.7  756.34   223.1  756.15   252.1  754.85   271.3  752.26   280.9  751.15
   290.5  750.78   319.3  750.32   338.5  749.44   348.1  747.66     355  746.68
   357.7  746.29   367.3  746.45     370  747.52   376.9  750.27   396.1   765.1
   415.2  776.66   434.4  787.86     444  793.28   453.6  798.19   472.8  806.25
#Mann= 3 , 0 , 0
       0      .1       0     355    .045       0     370      .1       0
#XS Ineff= 2 , 0
       0     327     760               0
Permanent Ineff=
       F       F
Bank Sta=355,370
XS Rating Curve= 0 ,0
Exp/Cntr=0.3,0.1

Type RM Length L Ch R = 1 ,12649.3 ,152.3,151.8,151.4
XS GIS Cut Line= 2
     1801196.796      436256.048     1801612.377      436253.877
#Sta/Elev= 30
       0  775.37     9.7  771.92    19.3  769.94    38.7   767.1    48.3  765.91
      58  765.06    96.6  762.69   106.3  761.69     116  760.41   125.6  759.34
   135.3   758.7     145  758.27   164.3  757.48   183.6  757.11   193.3  757.31
   212.6  758.38   222.3  758.16   241.6  756.45   270.6  754.22   309.3  751.65
   323.5  747.47   328.6  746.05   338.3  745.92  340.12  747.04   347.9  750.92
   357.6  758.44   367.3  764.97   386.6  776.89   405.9  788.36   415.6  793.98
#Mann= 3 , 0 , 0
       0      .1       0   323.5    .045       0  340.12      .1       0
Bank Sta=323.5,340.12
XS Rating Curve= 0 ,0
Exp/Cntr=0.3,0.1

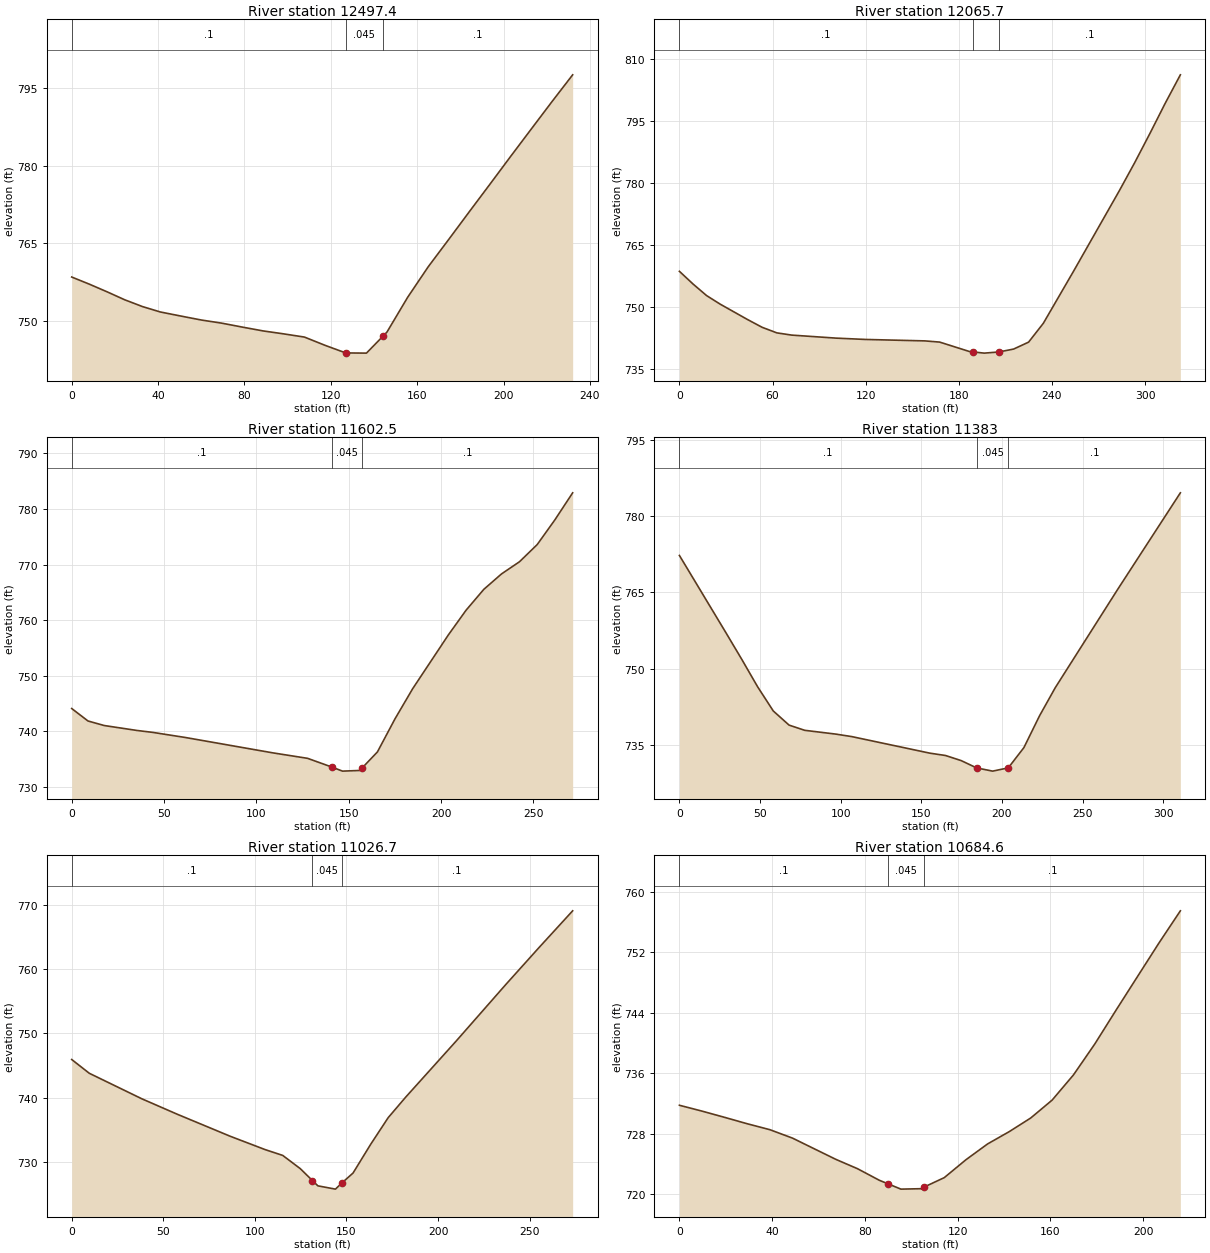
Type RM Length L Ch R = 1 ,12497.4 ,420.9,431.7,442.6
XS GIS Cut Line= 3
     1801395.363      436386.256     1801430.086      436407.957
     1801621.058      436403.617
#Sta/Elev= 28
       0  758.45     8.2  757.06    16.4  755.58    24.6  754.03    32.8  752.72
      41  751.68    50.5  750.89      60  750.12    69.6   749.5    79.2  748.73
    88.7     748    98.2  747.43   107.8  746.81   117.4   745.2   126.9  743.74
   129.1  743.73   136.5   743.7   144.1  746.96     146  747.78   155.6  754.53
   165.1  760.43   174.7  765.79   184.2  771.14   193.8   776.5   203.3  781.84
   212.9  787.17   222.4  792.43     232  797.64
#Mann= 3 , 0 , 0
       0      .1       0   126.9    .045       0   144.1      .1       0
Bank Sta=126.9,144.1
XS Rating Curve= 0 ,0
Exp/Cntr=0.3,0.1

Type RM Length L Ch R = 1 ,12065.7 ,468.2,463.2,457.9
XS GIS Cut Line= 4
     1801323.749      436742.159     1801361.726       436763.86
     1801534.252       436845.24     1801616.717      436876.707
#Sta/Elev= 25
       0   758.6     8.8  755.52    17.5  752.73    26.2  750.67    43.7  746.97
    53.3  745.05    62.8   743.7    72.4  743.16     101  742.43     120  742.11
   158.2  741.76   167.7  741.47   186.8   739.2   189.1   739.1   196.4   738.8
   205.9  739.08   215.4  739.79     225  741.46   234.5  746.02   254.1  758.71
   283.5  778.13   293.3  784.85   303.2  791.98     313  799.25   322.8  806.16
#Mann= 3 , 0 , 0
       0      .1       0   189.1    .045       0   205.9      .1       0
Bank Sta=189.1,205.9
XS Rating Curve= 0 ,0
Exp/Cntr=0.3,0.1

Type RM Length L Ch R = 1 ,11602.5 ,225.6,219.5,213.5
XS GIS Cut Line= 4
     1801284.686      437257.567      1801345.45      437267.332
     1801456.127      437292.289     1801551.613      437304.225
#Sta/Elev= 23
       0   744.1     8.8  741.86    17.6  741.04    35.2  740.16      44   739.8
    61.5  738.89   108.8  736.13   127.7  735.14   141.1  733.54   146.6  732.84
   156.1  732.96  157.31  733.44   165.5  736.29     175  742.23   184.6  747.67
   203.9  757.33   213.5  761.78   223.1  765.53   232.7  768.31   242.4  770.49
     252  773.58   261.6  778.04   271.2  782.89
#Mann= 3 , 0 , 0
       0      .1       0   141.1    .045       0  157.31      .1       0
Bank Sta=141.1,157.31
XS Rating Curve= 0 ,0
Exp/Cntr=0.3,0.1

Type RM Length L Ch R = 1 ,11383   ,355.4,356.3,356.8
XS GIS Cut Line= 2
     1801219.582      437512.558     1801529.912      437498.452
#Sta/Elev= 20
       0  772.22    29.1   756.9    38.8  751.73    48.5  746.41    58.2  741.66
      68  738.88    77.7  737.86    97.1  737.11   106.8  736.63   155.3  733.37
     165  732.91   174.7  731.91   184.3  730.47   194.2  729.84   203.9  730.48
   213.6  734.47   223.3  740.72     233  746.22   271.8  765.59   310.6  784.53
#Mann= 3 , 0 , 0
       0      .1       0   184.3    .045       0   203.9      .1       0
Bank Sta=184.3,203.9
XS Rating Curve= 0 ,0
Exp/Cntr=0.3,0.1

Type RM Length L Ch R = 1 ,11026.7 ,345,342.1,339
XS GIS Cut Line= 3
     1801269.495      437847.844     1801451.787      437842.419
     1801540.763       437861.95
#Sta/Elev= 20
       0  745.95     9.6  743.81    38.4  739.83    57.6  737.45    86.4  734.04
   105.6  731.95   115.2  731.05   124.8  728.99   131.4  727.15   134.4  726.32
     144  725.81  147.48  726.76   153.6  728.31   163.2  732.76   172.8  736.92
   182.4  740.12   209.7  748.75     237   757.6   255.2  763.36   273.5  769.05
#Mann= 3 , 0 , 0
       0      .1       0   131.4    .045       0  147.48      .1       0
Bank Sta=131.4,147.48
XS Rating Curve= 0 ,0
Exp/Cntr=0.3,0.1

Type RM Length L Ch R = 1 ,10684.6 ,307.8,323.2,338.2
XS GIS Cut Line= 4
     1801359.556       438172.28     1801405.129      438189.641
      1801497.36       438174.45     1801563.549      438141.898
#Sta/Elev= 26
       0  731.77     9.8  730.99    19.5  730.17    29.3  729.32      39  728.54
    48.8  727.42    58.1  726.02    67.5  724.61    76.8  723.38    86.2  721.85
    89.8   721.4    95.5  720.68   104.8  720.74  105.62  720.97   114.2   722.2
   123.6  724.58   132.9  726.66   142.2  728.28   151.5  730.09   160.7  732.45
   169.9  735.78   179.1  739.87   188.3  744.36   197.6  748.83   206.8  753.24
     216  757.48
#Mann= 3 , 0 , 0
       0      .1       0    89.8    .045       0  105.62      .1       0
Bank Sta=89.8,105.62
XS Rating Curve= 0 ,0
Exp/Cntr=0.3,0.1

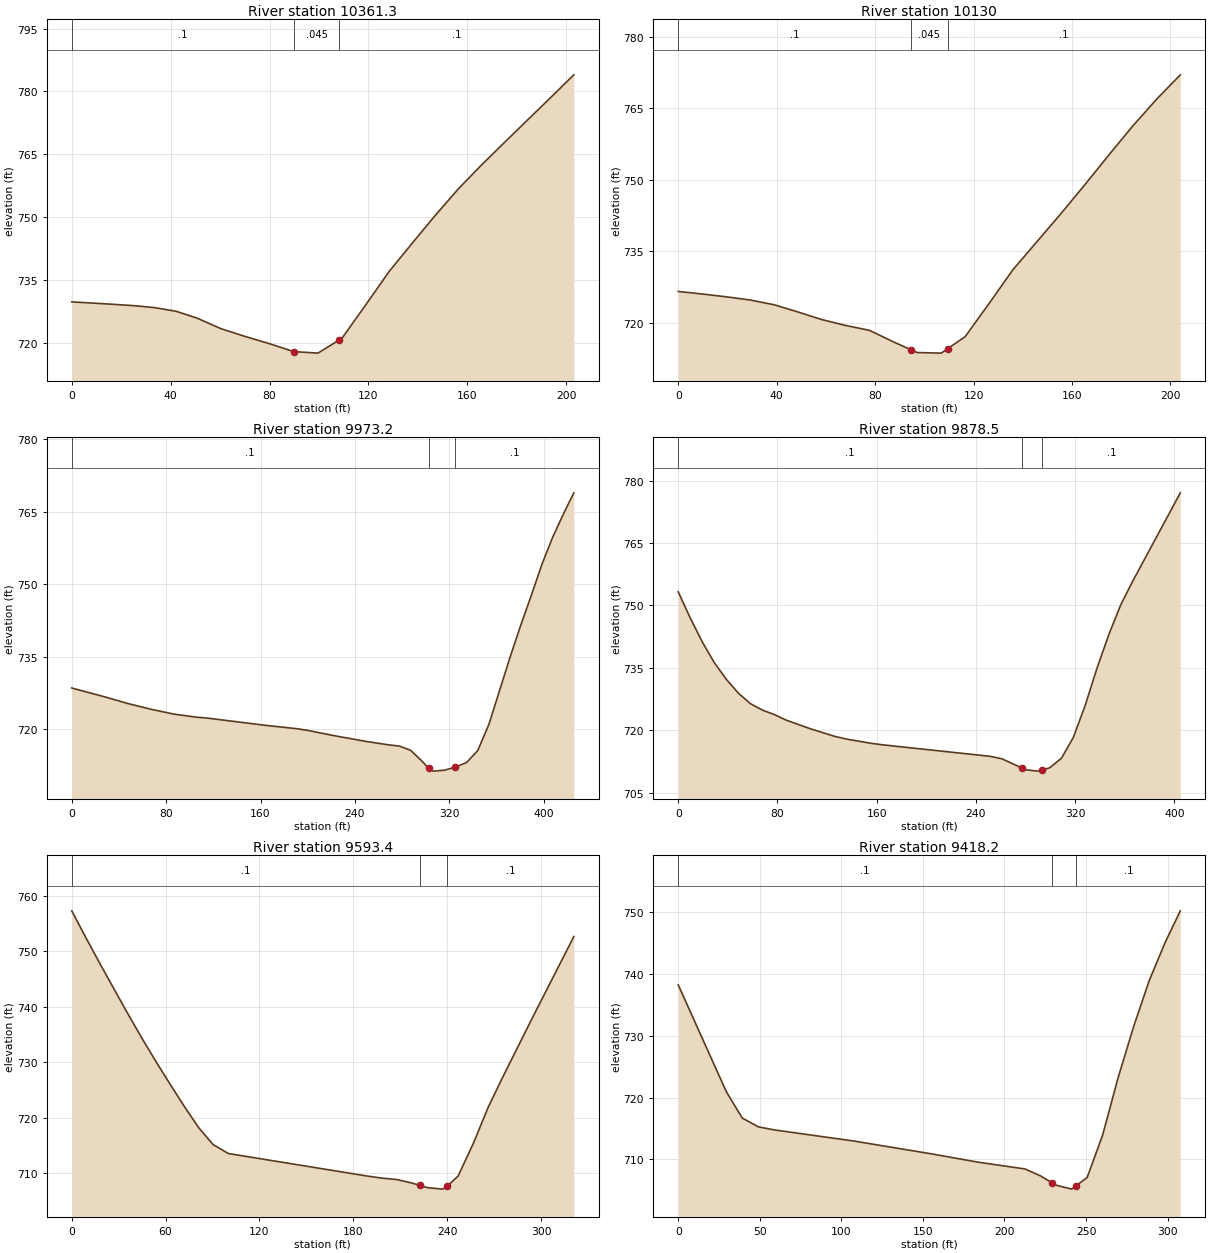
Type RM Length L Ch R = 1 ,10361.3 ,243,231.3,219.4
XS GIS Cut Line= 4
     1801362.811      438448.973     1801406.214      438475.015
     1801465.893      438508.652     1801540.763      438546.629
#Sta/Elev= 25
       0  729.73     8.4  729.44    16.9  729.14    25.3  728.82    33.7  728.34
    42.2  727.48    50.6  725.87    60.4  723.32    70.2  721.46      80  719.74
    89.8  717.85    93.2  717.73    99.6  717.49   108.2  720.63   109.3  721.03
   119.1  729.17   128.4     737   137.8   743.8   147.1  750.42   156.4  756.73
   165.8  762.45   175.1  767.84   184.4  773.18   193.7  778.51   203.1  783.95
#Mann= 3 , 0 , 0
       0      .1       0    89.8    .045       0   108.2      .1       0
Bank Sta=89.8,108.2
XS Rating Curve= 0 ,0
Exp/Cntr=0.3,0.1

Type RM Length L Ch R = 1 ,10130   ,168.1,156.8,145.6
XS GIS Cut Line= 2
     1801252.134       438709.39     1801456.127      438708.304
#Sta/Elev= 24
       0  726.61     9.7  726.08    19.4  725.49    29.1  724.83    38.9  723.83
    48.6  722.32    58.3  720.72      68  719.49    77.7  718.46    87.4  716.06
    94.5  714.41    97.1  713.81   106.9  713.69   109.5  714.62   116.6  717.15
   126.3  724.09     136  731.17   145.7  737.01   155.4  742.85   165.1   748.9
   174.8  755.09   184.6  761.22   194.3  766.84     204  771.99
#Mann= 3 , 0 , 0
       0      .1       0    94.5    .045       0   109.5      .1       0
Bank Sta=94.5,109.5
XS Rating Curve= 0 ,0
Exp/Cntr=0.3,0.1

Type RM Length L Ch R = 1 ,9973.2  ,98.2,94.7,91.2
XS GIS Cut Line= 4
     1801055.737      438880.831     1801333.514      438880.831
     1801399.704      438843.938     1801459.382      438803.791
#Sta/Elev= 30
       0  728.51    28.7  726.62    47.9  725.27      67  724.12    86.2  723.12
   105.4  722.48   114.9  722.28   162.8  720.82   191.6  720.06   201.2  719.68
   220.3  718.74     249  717.47   268.2  716.76   277.8  716.48   287.2  715.62
   296.7   713.4  302.48  711.91   306.2  711.31   315.7   711.5   324.6  712.09
   334.6  713.09   344.1  715.58   353.6  721.04   371.5  734.91   380.5  741.47
   389.5   747.7   398.5  754.11   407.5  759.66   416.5  764.42   425.5  768.88
#Mann= 3 , 0 , 0
       0      .1       0  302.48    .045       0   324.6      .1       0
Bank Sta=302.48,324.6
XS Rating Curve= 0 ,0
Exp/Cntr=0.3,0.1

Type RM Length L Ch R = 1 ,9878.5  ,288.2,285.2,282.1
XS GIS Cut Line= 3
     1801197.881      439117.376      1801341.11      439001.273
     1801514.721       438865.64
#Sta/Elev= 30
       0  753.25     9.7  746.95    19.4   741.2    29.1  736.23    38.8  732.22
    48.5   728.9    58.2  726.38    67.9  724.83    77.6  723.74    87.3  722.39
   106.7  720.33   126.2  718.52   135.9  717.86   155.3  716.86     165  716.48
   251.4  713.73     261  713.12   276.9  710.94   280.2   710.5   289.7  710.17
  293.58  710.49   299.3  710.94   308.9  713.27   318.5  718.28   328.1  726.02
   337.6  734.95   347.2  743.08   356.8   750.2   366.4  755.84   404.7  777.04
#Mann= 3 , 0 , 0
       0      .1       0   276.9    .045       0  293.58      .1       0
Bank Sta=276.9,293.58
XS Rating Curve= 0 ,0
Exp/Cntr=0.3,0.1

Type RM Length L Ch R = 1 ,9593.4  ,175.1,175.2,174.9
XS GIS Cut Line= 4
     1801487.594      439320.284     1801526.657      439238.903
     1801642.759      439119.546     1801681.822      439068.548
#Sta/Elev= 26
       0  757.33       9   752.5      18  747.82    27.1  743.19    36.1  738.65
    45.1  734.24    54.2  729.98    63.2  725.92    72.2  721.96    81.2  718.21
    90.3   715.2   100.1  713.57   188.2  709.54     198  709.14   207.8  708.88
   217.6  708.24   222.7  707.81   227.4  707.42   237.2  707.15  239.95  707.65
     247  709.51   256.8  715.43     266  721.76   275.1   727.1   293.5  737.48
     321  752.69
#Mann= 3 , 0 , 0
       0      .1       0   222.7    .045       0  239.95      .1       0
Bank Sta=222.7,239.95
XS Rating Curve= 0 ,0
Exp/Cntr=0.3,0.1

Type RM Length L Ch R = 1 ,9418.2  ,397.4,411.1,425
XS GIS Cut Line= 3
      1801576.57      439381.048     1801667.716      439344.155
     1801813.115      439193.331
#Sta/Elev= 21
       0  738.21    29.5  720.93    39.3  716.67    49.2  715.25      59  714.76
   107.8  712.96   155.5  710.88     184  709.54   212.6  708.45   222.1  707.33
   229.1  706.22   231.6  705.83   241.2  705.19   244.1  705.76   250.7  707.07
   260.2  713.94   269.7  723.23   279.3  731.56   288.8  738.94   298.3  744.95
   307.8  750.18
#Mann= 3 , 0 , 0
       0      .1       0   229.1    .045       0   244.1      .1       0
Bank Sta=229.1,244.1
XS Rating Curve= 0 ,0
Exp/Cntr=0.3,0.1

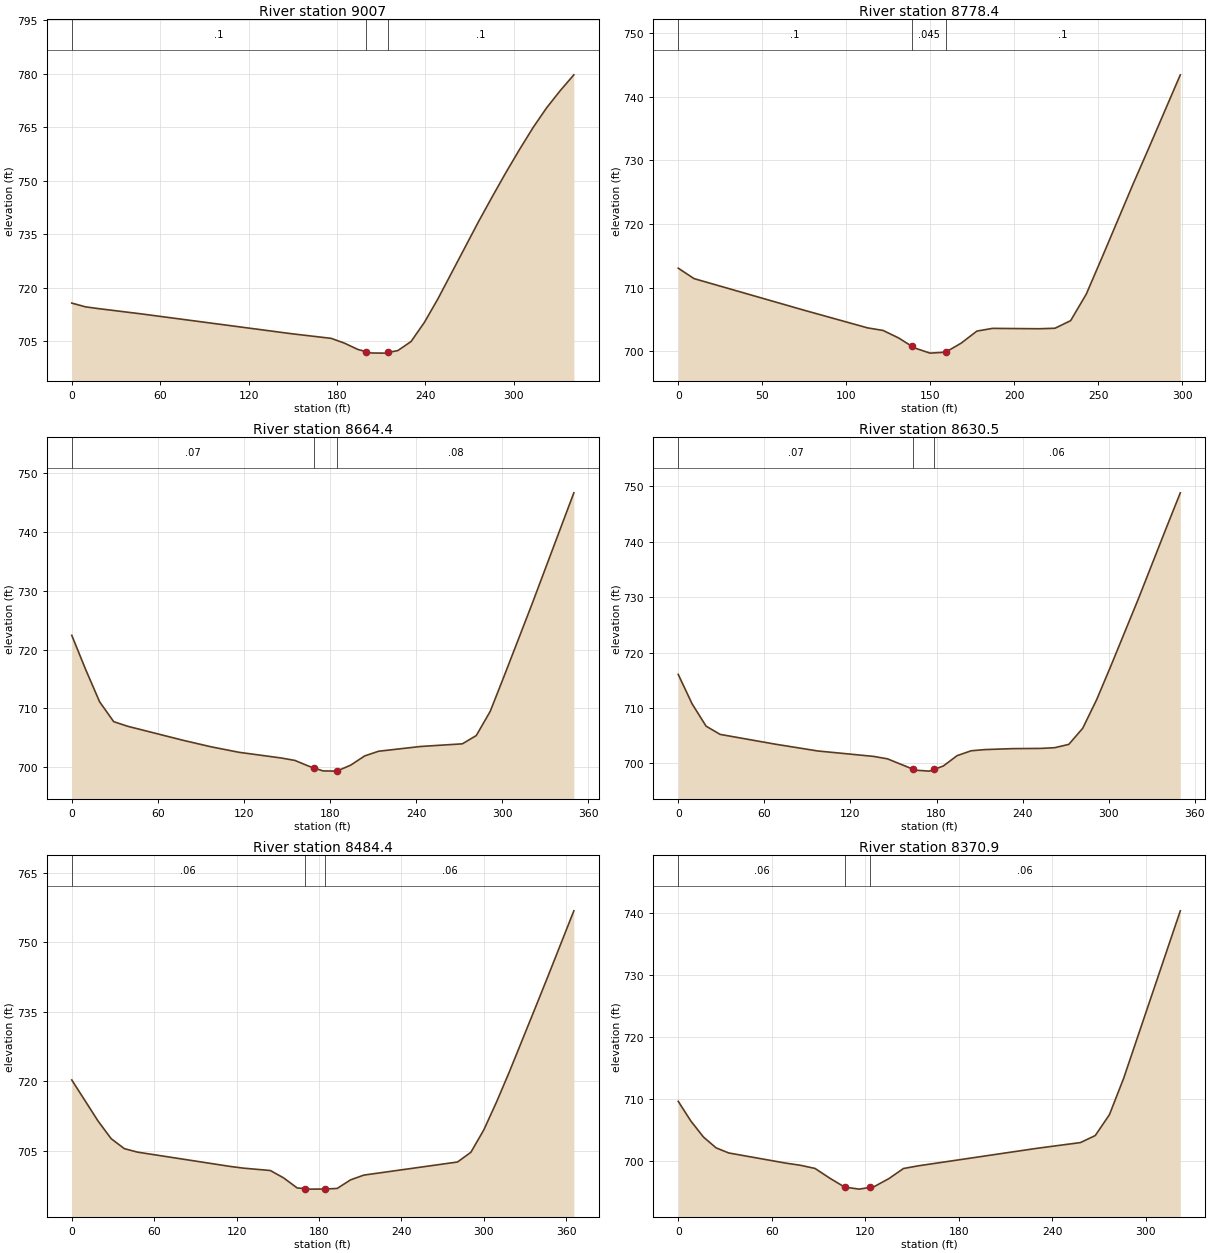
Type RM Length L Ch R = 1 ,9007    ,234.6,228.6,222.5
XS GIS Cut Line= 4
     1801719.799      439617.593     1801859.773      439616.508
     1801957.429      439598.061     1802048.575      439553.574
#Sta/Elev= 24
       0  715.74     9.3  714.69    18.7  714.16    46.7  712.74     149  707.16
   176.1  705.85   185.2  704.49   194.2  702.74   199.8  702.12   203.2  701.75
   212.3  701.71   214.8  701.91   221.3  702.42   230.3  704.96   239.4  710.36
   248.6  716.98   276.2  738.66   285.5  745.63   294.7  752.36   303.9  758.79
   313.1  764.94   322.3  770.49   331.6  775.34   340.8  779.75
#Mann= 3 , 0 , 0
       0      .1       0   199.8    .045       0   214.8      .1       0
Bank Sta=199.8,214.8
XS Rating Curve= 0 ,0
Exp/Cntr=0.3,0.1

Type RM Length L Ch R = 1 ,8778.4  ,115.3,114.1,112.8
XS GIS Cut Line= 4
      1801809.86      439870.414      1801884.73      439860.648
     1802034.469      439785.778     1802082.212      439756.482
#Sta/Elev= 21
       0  713.07     9.4  711.43    75.5  706.42   112.7  703.69     122  703.28
   131.3  702.09   138.9  700.82   140.6  700.54   149.9  699.72   159.2  699.87
   168.5   701.3   177.8  703.18   187.1  703.61     215  703.55   224.3  703.63
   233.6  704.82   242.9  708.98   252.2  714.69   270.9  726.36   280.3  732.04
   298.9  743.45
#Mann= 3 , 0 , 0
       0      .1       0   138.9    .045       0   159.2      .1       0
Bank Sta=138.9,159.2
XS Rating Curve= 0 ,0
Exp/Cntr=0.3,0.1

Type RM Length L Ch R = 1 ,8664.4  ,33.8,33.8,33.8
XS GIS Cut Line= 2
     1801844.582      440019.068     1802148.401      439845.457
#Sta/Elev= 25
       0  722.44     9.7  716.62    19.4  711.14    29.2  707.77    38.9  706.98
    77.8  704.58    97.2  703.48   116.6  702.55   145.8  701.59   155.5  701.17
   165.2  700.19     169  699.88     175  699.39     184  699.35   184.7  699.35
   194.4  700.37   204.1  701.93   213.8  702.73     243  703.54   272.2  703.99
   281.9   705.4   291.6   709.5   301.3   715.5   320.8  727.79   349.9  746.67
#Mann= 3 , 0 , 0
       0     .07       0     169    .045       0   184.7     .08       0
Bank Sta=169,184.7
XS Rating Curve= 0 ,0
Exp/Cntr=0.3,0.1

Type RM Length L Ch R = 1 ,8630.5  ,136,146.2,156
XS GIS Cut Line= 2
     1801865.198      440046.195     1802169.018      439872.584
#Sta/Elev= 26
       0  716.08     9.7  710.75    19.4  706.74    29.2  705.25      68  703.47
    97.2  702.26   136.1  701.28   145.8  700.84   163.3     699   165.2  698.79
     175  698.62   178.3  698.93   184.7  699.54   194.4  701.42   204.1  702.29
   213.8  702.51   233.3  702.68   252.7  702.72   262.4  702.85   272.2  703.45
   281.9  706.36   291.6  711.52   301.3  717.48   320.8   729.8   340.2  742.57
   349.9  748.85
#Mann= 3 , 0 , 0
       0     .07       0   163.3    .045       0   178.3     .06       0
Bank Sta=163.3,178.3
XS Rating Curve= 0 ,0
Exp/Cntr=0.3,0.1

Type RM Length L Ch R = 1 ,8484.4  ,116.2,113.5,110.2
XS GIS Cut Line= 4
     1801873.879      440089.598     1801959.599      440098.278
     1802163.592      440084.173     1802236.292      440065.726
#Sta/Elev= 24
       0  720.28    19.2  711.39    28.7  707.59    38.3  705.44    47.9  704.69
   115.4   701.6   125.1  701.23   144.6  700.72   154.3  699.12   164.1  696.96
   169.5  696.82   173.8   696.7   184.5  696.72   193.3  696.85     203   698.7
   212.7  699.73   280.9  702.56   290.6  704.65     300  709.47   309.4  715.58
   318.8  722.15   337.5  735.84   346.9  742.78   365.6  756.81
#Mann= 3 , 0 , 0
       0     .06       0   169.5    .045       0   184.5     .06       0
Bank Sta=169.5,184.5
XS Rating Curve= 0 ,0
Exp/Cntr=0.3,0.1

Type RM Length L Ch R = 1 ,8370.9  ,76.3,76.3,76.8
XS GIS Cut Line= 4
     1801907.516      440212.211     1801947.664      440217.636
     1802169.018      440166.638     1802223.271      440160.127
#Sta/Elev= 22
       0  709.67     8.1   706.5    16.2  703.92    24.3  702.18    32.4  701.36
    68.9  699.73    78.4  699.38    87.8  698.87    97.3   697.3   106.8  695.87
   116.2  695.54   123.1  695.82   125.7  695.93   135.2  697.23   144.6  698.86
   154.1  699.29   229.8  702.09   258.2  703.03   267.7  704.16   276.8  707.52
   285.9  713.35   322.3  740.32
#Mann= 3 , 0 , 0
       0     .06       0   106.8    .045       0   123.1     .06       0
Bank Sta=106.8,123.1
XS Rating Curve= 0 ,0
Exp/Cntr=0.3,0.1

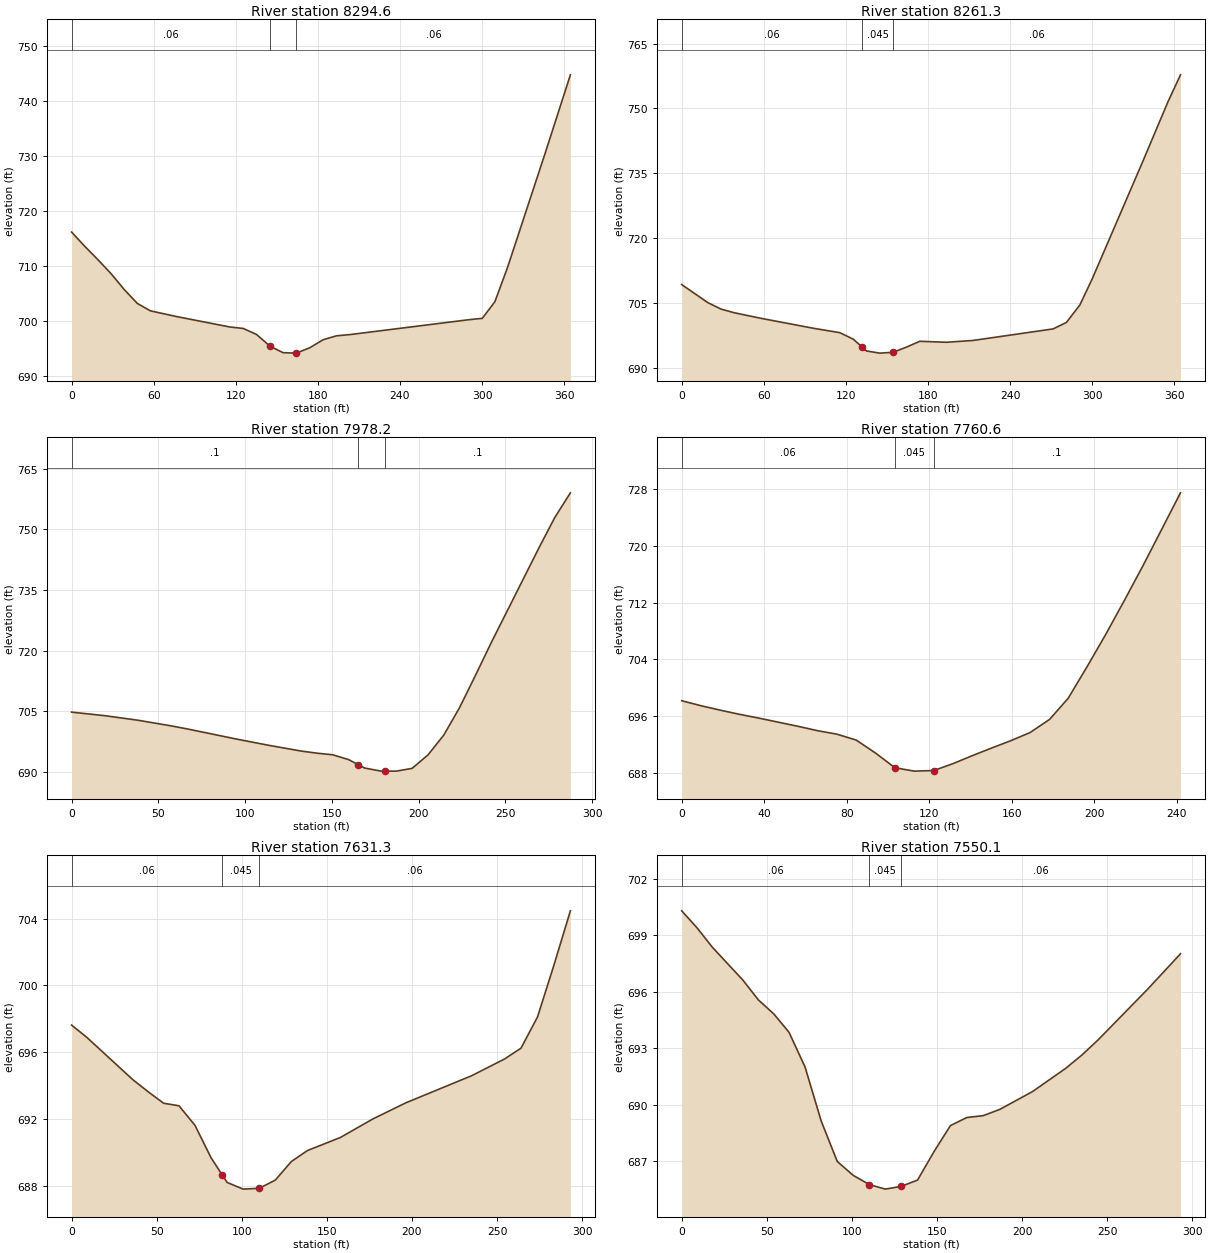
Type RM Length L Ch R = 1 ,8294.6  ,33.2,33.3,33.2
XS GIS Cut Line= 4
     1801870.624       440280.57     1801956.344      440291.421
     1802155.997      440246.933     1802228.697      440258.869
#Sta/Elev= 24
       0  716.11     9.6  713.53    19.2   711.1    28.8  708.56    38.4  705.68
      48  703.14    57.6  701.78    76.8  700.74   115.6  698.85   125.4  698.58
   135.1   697.5     145  695.36   154.6  694.17   164.3  694.09   174.1  695.07
   183.8  696.52   193.6  697.24   203.3  697.46     291  700.19   300.2  700.42
   309.4  703.44   318.6  709.63   346.2  730.49   364.6  744.72
#Mann= 3 , 0 , 0
       0     .06       0     145    .045       0   164.3     .06       0
Bank Sta=145,164.3
XS Rating Curve= 0 ,0
Exp/Cntr=0.3,0.1

Type RM Length L Ch R = 1 ,8261.3  ,282.5,283.1,283.6
XS GIS Cut Line= 4
     1801885.815      440310.952     1801971.535      440321.803
     1802171.188      440277.315     1802243.888      440289.251
#Sta/Elev= 23
       0  709.27    19.2  705.08    28.8   703.6    38.4  702.76    57.6  701.49
    96.1  699.18   115.6  698.15   125.4  696.65   132.1  694.76   135.1  693.92
   144.8  693.42   154.6  693.61   164.3  694.81   174.1  696.16   193.6  695.93
     213  696.35   271.5  699.02   281.2  700.51     291  704.52   300.2  710.67
     337   737.7   355.4  751.49   364.6  757.77
#Mann= 3 , 0 , 0
       0     .06       0   132.1    .045       0   154.6     .06       0
Bank Sta=132.1,154.6
XS Rating Curve= 0 ,0
Exp/Cntr=0.3,0.1

Type RM Length L Ch R = 1 ,7978.2  ,220,217.6,214.3
XS GIS Cut Line= 4
     1801922.707      440614.771     1802025.789       440595.24
     1802133.211      440573.539      1802205.91      440568.114
#Sta/Elev= 25
       0  704.84    19.1  703.97    38.2  702.84    57.2  701.46    66.8  700.68
    95.4  698.15     114  696.61   132.3  695.22   141.4   694.7   150.6  694.29
   159.7  693.09   165.3  691.82   168.8  691.03     178  690.28   180.3  690.27
   187.1  690.26   196.2  690.94   205.4  694.29   214.5   699.2   223.6     706
   232.7  713.92   241.8  722.02   269.2  745.37   278.3  752.86   287.4  759.05
#Mann= 3 , 0 , 0
       0      .1       0   165.3    .045       0   180.3      .1       0
Bank Sta=165.3,180.3
XS Rating Curve= 0 ,0
Exp/Cntr=0.3,0.1

Type RM Length L Ch R = 1 ,7760.6  ,113.5,129.4,146.1
XS GIS Cut Line= 4
     1802007.342      440813.339     1802063.766      440811.169
     1802179.869      440774.277     1802229.782      440735.214
#Sta/Elev= 28
       0  698.18     9.4  697.47    18.8  696.84    28.2  696.25    37.6  695.71
      47  695.14    56.5  694.56    65.8  693.95    75.2  693.46    84.6  692.62
      94  690.78   103.3  688.72   112.7  688.24   118.3  688.29   122.1  688.32
   131.4  689.29   140.8  690.42   150.2   691.5   159.6  692.55   168.9   693.7
   178.3  695.55   187.3  698.53   196.4  702.96   205.4   707.5   214.5  712.33
   223.6  717.28   232.6  722.37   241.7  727.53
#Mann= 3 , 0 , 0
       0     .06       0   103.3    .045       0   122.1      .1       0
Bank Sta=103.3,122.1
XS Rating Curve= 0 ,0
Exp/Cntr=0.3,0.1

Type RM Length L Ch R = 1 ,7631.3  ,81.1,81.1,79.4
XS GIS Cut Line= 4
     1802035.554      440871.933     1802083.297      440913.166
     1802154.912      440937.037     1802289.461      440861.082
#Sta/Elev= 24
       0  697.62       9  696.88      36  694.35    45.1  693.62    54.1  692.94
    63.1  692.79    72.5  691.62      82  689.67    88.5  688.65    91.4   688.2
   100.8   687.8   110.3  687.85   119.7  688.34   129.1  689.45   138.6  690.11
   157.9  690.89   177.2  692.01   196.5  692.97   235.1  694.59   254.4  695.59
   264.1  696.24   273.8  698.11   283.4   701.2   293.1  704.46
#Mann= 3 , 0 , 0
       0     .06       0    88.5    .045       0   110.3     .06       0
Bank Sta=88.5,110.3
XS Rating Curve= 0 ,0
Exp/Cntr=0.3,0.1

Type RM Length L Ch R = 1 ,7550.1  ,118.2,92,67.9
XS GIS Cut Line= 4
      1802040.98      440944.633     1802088.723      440985.865
     1802160.337      441009.737     1802294.886      440933.782
#Sta/Elev= 26
       0   700.3       9   699.4      18  698.37      36  696.62    45.1  695.57
    54.1  694.83    63.1  693.85    72.5  692.01      82  689.14    91.4     687
   100.8  686.26   110.3  685.77   119.7  685.53   129.1  685.68   138.6  686.01
   148.2  687.51   157.9   688.9   167.5  689.33   177.2  689.43   186.9  689.76
   206.2  690.71   225.5  691.93   235.1  692.64   244.8  693.46   273.8  696.14
   293.1  698.02
#Mann= 3 , 0 , 0
       0     .06       0   110.3    .045       0   129.1     .06       0
Bank Sta=110.3,129.1
XS Rating Curve= 0 ,0
Exp/Cntr=0.3,0.1