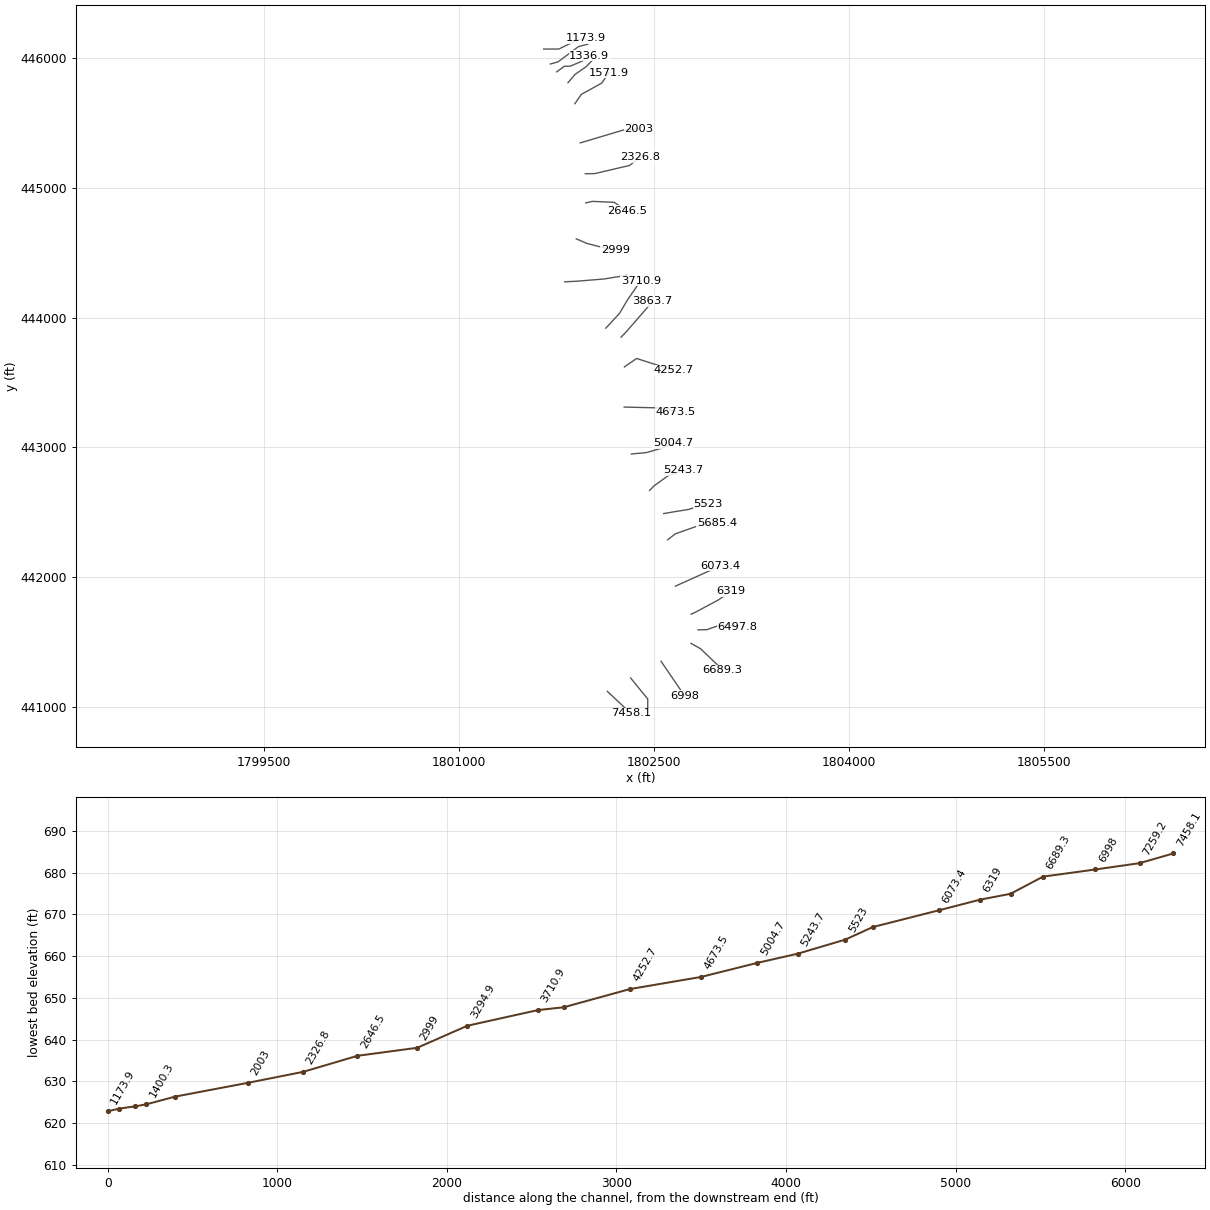
HEC-RAS study LEFTFORK2.prj: LEFTFORK2

--- LEFTFORK2.g01 (geometry) --- (continued)

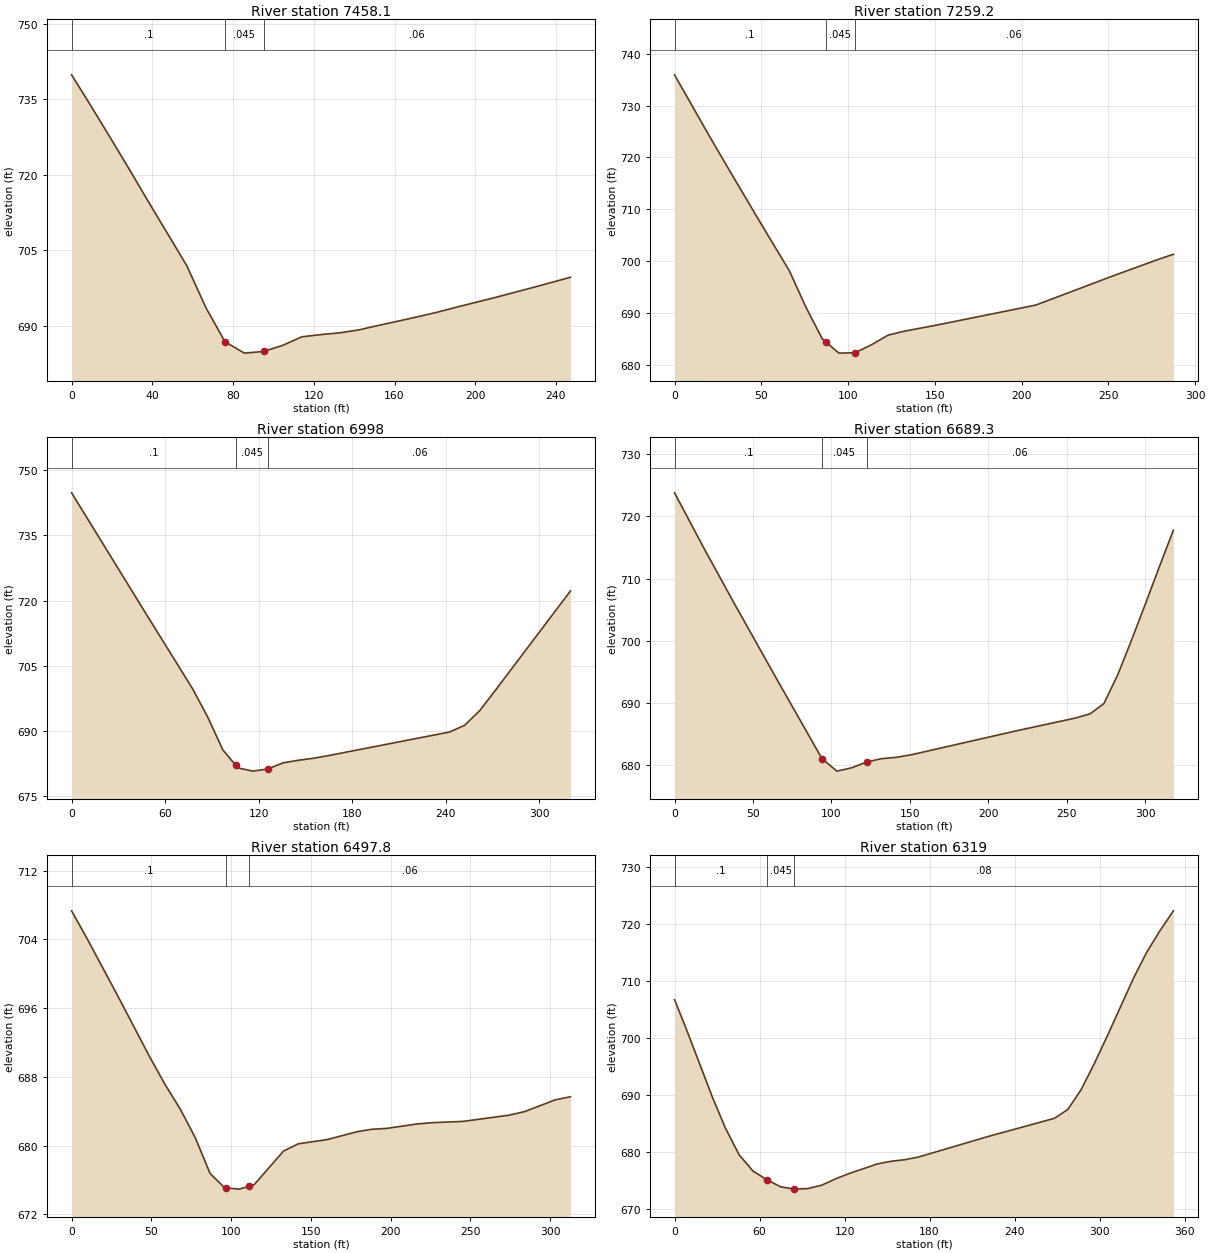
Type RM Length L Ch R = 1 ,7458.1  ,201.7,198.9,195.6
XS GIS Cut Line= 2
     1802140.806      441121.499     1802320.928      440952.228
#Sta/Elev= 29
       0  739.85     9.5  733.73      19  727.48    28.5  721.16      38   714.7
    47.5  708.36      57  702.02    66.6   693.6    73.3   688.8      76  686.87
    85.6  684.61    88.3   684.7    95.1  684.94   104.6  686.15   114.1  687.85
   123.6  688.29   133.1  688.65   142.6  689.24   152.1  690.12   161.6  690.94
   171.1  691.79   180.6  692.67   190.1  693.66   199.6  694.62   209.2  695.58
   218.7  696.59   228.2  697.59   237.7  698.63   247.2  699.66
#Mann= 3 , 0 , 0
       0      .1       0      76    .045       0    95.1     .06       0
Bank Sta=76,95.1
XS Rating Curve= 0 ,0
Exp/Cntr=0.3,0.1

Type RM Length L Ch R = 1 ,7259.2  ,263.2,261.1,259.2
XS GIS Cut Line= 3
     1802319.842      441224.581     1802451.136      441062.905
     1802451.136      440983.695
#Sta/Elev= 18
       0  735.92    18.9   724.8    28.4  719.34    47.3  708.64    66.3  698.07
    75.7  691.14    85.2     685    87.1  684.46    94.7  682.28   104.1  682.36
   113.6  683.91   123.1  685.75   132.5  686.51   151.5  687.71   208.3  691.55
   252.3  697.12   278.7  700.34   287.5  701.33
#Mann= 3 , 0 , 0
       0      .1       0    87.1    .045       0   104.1     .06       0
Bank Sta=87.1,104.1
XS Rating Curve= 0 ,0
Exp/Cntr=0.3,0.1

Type RM Length L Ch R = 1 ,6998    ,300.7,308.8,313.5
XS GIS Cut Line= 2
     1802553.132      441353.704     1802733.254      441088.947
#Sta/Elev= 18
       0  744.79    48.5  716.54    77.6  699.74    87.3  693.25      97   685.7
   105.4  682.06   106.7   681.5   116.4  680.76   126.2  681.28   135.8  682.67
   145.6  683.26   155.3  683.72     165  684.34   242.6  689.76   252.3  691.31
     262   694.7   271.7  699.21   320.2  722.22
#Mann= 3 , 0 , 0
       0      .1       0   105.4    .045       0   126.2     .06       0
Bank Sta=105.4,126.2
XS Rating Curve= 0 ,0
Exp/Cntr=0.3,0.1

Type RM Length L Ch R = 1 ,6689.3  ,169.2,191.5,216.7
XS GIS Cut Line= 4
     1802783.167      441491.508     1802856.952      441450.275
      1802987.16      441325.492     1803021.882      441285.344
#Sta/Elev= 20
       0  723.77    18.8  714.84    37.6  706.21    65.7  693.59      94  681.05
   103.5  679.05     113  679.59   122.5  680.52     132  681.05   141.5  681.27
     151  681.68   217.4   685.5   255.4  687.57   264.9  688.26   273.7   689.9
   282.6  694.58   291.4  700.16   300.3  706.01   309.1  711.93     318  717.77
#Mann= 3 , 0 , 0
       0      .1       0      94    .045       0   122.5     .06       0
Bank Sta=94,122.5
XS Rating Curve= 0 ,0
Exp/Cntr=0.3,0.1

Type RM Length L Ch R = 1 ,6497.8  ,176.1,178.8,181.8
XS GIS Cut Line= 4
     1802837.421      441595.674      1802905.78      441596.759
     1803027.308      441640.162     1803140.155      441616.291
#Sta/Elev= 26
       0  707.31     9.8  704.05    29.3  697.29    48.8  690.38    58.6  687.11
    68.4  684.16    77.6   680.9    86.8  676.77      96  675.09    96.5  675.08
   105.2  674.94   111.5  675.29   114.5  675.46   132.9  679.37   142.1  680.21
   160.5  680.71     179  681.62   188.2   681.9   197.4     682   216.6  682.52
   226.2  682.67   245.5  682.82   274.3  683.54   283.9  683.95   303.2  685.32
   312.8  685.69
#Mann= 3 , 0 , 0
       0      .1       0    96.5    .045       0   111.5     .06       0
Bank Sta=96.5,111.5
XS Rating Curve= 0 ,0
Exp/Cntr=0.3,0.1

Type RM Length L Ch R = 1 ,6319    ,246.9,245.7,244.4
XS GIS Cut Line= 4
     1802785.337      441716.117     1802817.889      441731.308
     1802998.011      441827.879     1803088.072      441894.068
#Sta/Elev= 27
       0  706.79       9  701.18    26.9  689.56    35.9  684.26    45.6  679.56
    55.4   676.7    65.2  675.19    74.8  673.95    84.6  673.54    94.3  673.64
     104  674.24   113.8  675.36   123.5   676.3     143  677.95   152.7  678.42
   162.4   678.7   172.2  679.17   220.8  682.74   268.2  685.97   277.6  687.52
   286.9  690.96   296.2  695.53   305.5  700.44   324.1  710.64   333.4  715.16
   342.8  718.95   352.1  722.37
#Mann= 3 , 0 , 0
       0      .1       0    65.2    .045       0    84.6     .08       0
Bank Sta=65.2,84.6
XS Rating Curve= 0 ,0
Exp/Cntr=0.3,0.1

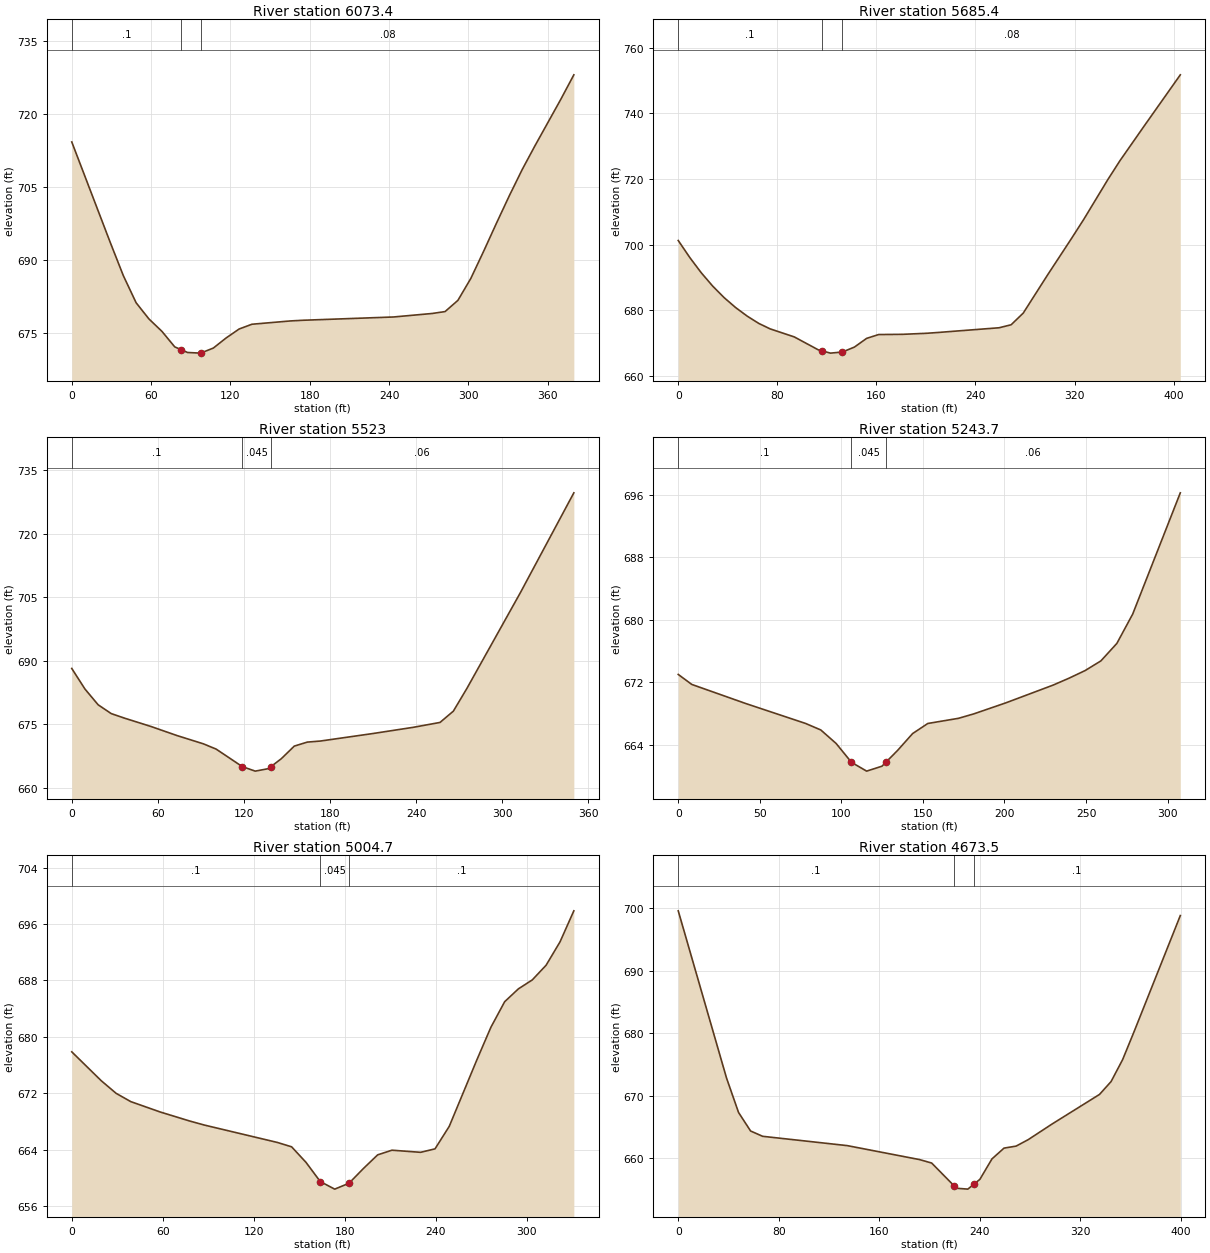
Type RM Length L Ch R = 1 ,6073.4  ,389.8,388,387.1
XS GIS Cut Line= 2
     1802663.809      441932.046     1803009.947      442088.296
#Sta/Elev= 29
       0  714.32    29.2  693.63      39  686.88    48.7   681.3    58.4  677.98
    68.2  675.44    77.9  672.25    82.9  671.66    87.6   671.1    97.4  670.97
    97.9  671.02   107.1  672.01   116.8  674.09   126.6  675.92   136.3   676.9
   165.5  677.58   175.3  677.72   243.4  678.39   272.7  679.11   282.4   679.5
   292.1   681.8   301.9  686.32   311.6   691.9   321.3  697.66   331.1  703.34
   340.8  708.69   350.6  713.64     370   723.1   379.8   728.1
#Mann= 3 , 0 , 0
       0      .1       0    82.9    .045       0    97.9     .08       0
Bank Sta=82.9,97.9
XS Rating Curve= 0 ,0
Exp/Cntr=0.3,0.1

Type RM Length L Ch R = 1 ,5685.4  ,166.5,162.4,157.3
XS GIS Cut Line= 4
     1802604.131      442289.034     1802662.724      442334.607
     1802846.101      442399.711     1802981.735      442415.987
#Sta/Elev= 30
       0  701.29     9.3  696.12    18.6  691.45    27.8   687.4    37.1  683.86
    46.4  680.84    55.7  678.24      65  676.03    74.2  674.36    93.7  671.91
   113.2  667.95   115.7   667.7   122.9  666.97   132.6  667.31   142.3  668.82
   152.1  671.46   161.8  672.63   181.3   672.7   200.7  673.02   210.4  673.28
   259.1   674.7   268.8  675.61   278.6  679.18   298.1  690.72   317.6  701.94
   327.4   707.7   346.9  719.86   356.6  725.57   376.2  736.16   405.4  751.77
#Mann= 3 , 0 , 0
       0      .1       0   115.7    .045       0   132.6     .08       0
Bank Sta=115.7,132.6
XS Rating Curve= 0 ,0
Exp/Cntr=0.3,0.1

Type RM Length L Ch R = 1 ,5523    ,268.6,279.3,289.9
XS GIS Cut Line= 4
     1802573.749      442490.857     1802655.129      442504.962
     1802762.551      442522.324     1802914.461      442567.896
#Sta/Elev= 24
       0   688.2     9.2  683.34    18.4  679.62    27.5  677.55    36.7  676.48
    55.1  674.52    73.4  672.36    91.7  670.42   100.7  669.16   118.9  665.03
   127.9  663.97     137  664.55   138.7  664.99   146.1  666.91   155.1  669.87
   164.2  670.82   173.3  671.07   210.1  672.85   238.1  674.31   256.7  675.46
     266  678.12   275.4  683.46   312.7  706.07     350  729.65
#Mann= 3 , 0 , 0
       0      .1       0   118.9    .045       0   138.7     .06       0
Bank Sta=118.9,138.7
XS Rating Curve= 0 ,0
Exp/Cntr=0.3,0.1

Type RM Length L Ch R = 1 ,5243.7  ,246.9,239,231.1
XS GIS Cut Line= 4
     1802465.242      442668.808     1802499.964      442704.615
     1802606.301      442781.655     1802725.658      442823.973
#Sta/Elev= 23
       0  672.98     8.3   671.7    41.6  669.24      78  666.71    87.4  665.87
    96.8  664.14   106.2  661.73   115.5   660.6   124.9  661.23   127.3  661.74
   134.3  663.21   143.7  665.41     153   666.7   171.8  667.36   181.2  667.93
   200.7  669.33   229.9  671.62   239.6   672.5   249.4  673.47   259.1  674.71
   268.9  676.95   278.6   680.7   307.8  696.23
#Mann= 3 , 0 , 0
       0      .1       0   106.2    .045       0   127.3     .06       0
Bank Sta=106.2,127.3
XS Rating Curve= 0 ,0
Exp/Cntr=0.3,0.1

Type RM Length L Ch R = 1 ,5004.7  ,338.1,331.2,324.2
XS GIS Cut Line= 4
     1802325.268      442949.841      1802441.37      442960.692
     1802568.323      442997.584     1802643.193      443031.221
#Sta/Elev= 27
       0  677.87    19.4  673.78    29.2  671.99    38.9  670.81    58.3  669.34
    77.7  668.06    87.5  667.48   135.5  665.02   144.9   664.4   154.4  662.19
   163.8  659.47   173.3   658.4   182.7  659.23   192.2  661.32   201.6  663.26
     211  663.92   229.9  663.62   239.4  664.11   248.8  667.31     267  676.74
   276.2  681.34   285.3  684.98   294.4  686.81   303.5  688.07   312.6  690.15
   321.8  693.47   330.9  697.87
#Mann= 3 , 0 , 0
       0      .1       0   163.8    .045       0   182.7      .1       0
Bank Sta=163.8,182.7
XS Rating Curve= 0 ,0
Exp/Cntr=0.3,0.1

Type RM Length L Ch R = 1 ,4673.5  ,427,420.8,414.2
XS GIS Cut Line= 3
     1802269.929      443311.169      1802586.77      443303.574
     1802664.895      443276.447
#Sta/Elev= 23
       0  699.61    38.4  672.85      48  667.31    57.6  664.34    67.2  663.49
   134.5     662   192.1  659.76   201.7  659.21  219.31  655.61   220.9  655.18
   230.5  655.03   235.2   655.8   240.1   656.6   249.7  659.87   259.3   661.6
   268.9  661.92   278.5  662.95   297.7  665.48   335.3   670.2   344.5  672.26
   353.7  675.78   362.9   680.3   399.6  698.85
#Mann= 3 , 0 , 0
       0      .1       0  219.31    .045       0   235.2      .1       0
Bank Sta=219.31,235.2
XS Rating Curve= 0 ,0
Exp/Cntr=0.3,0.1

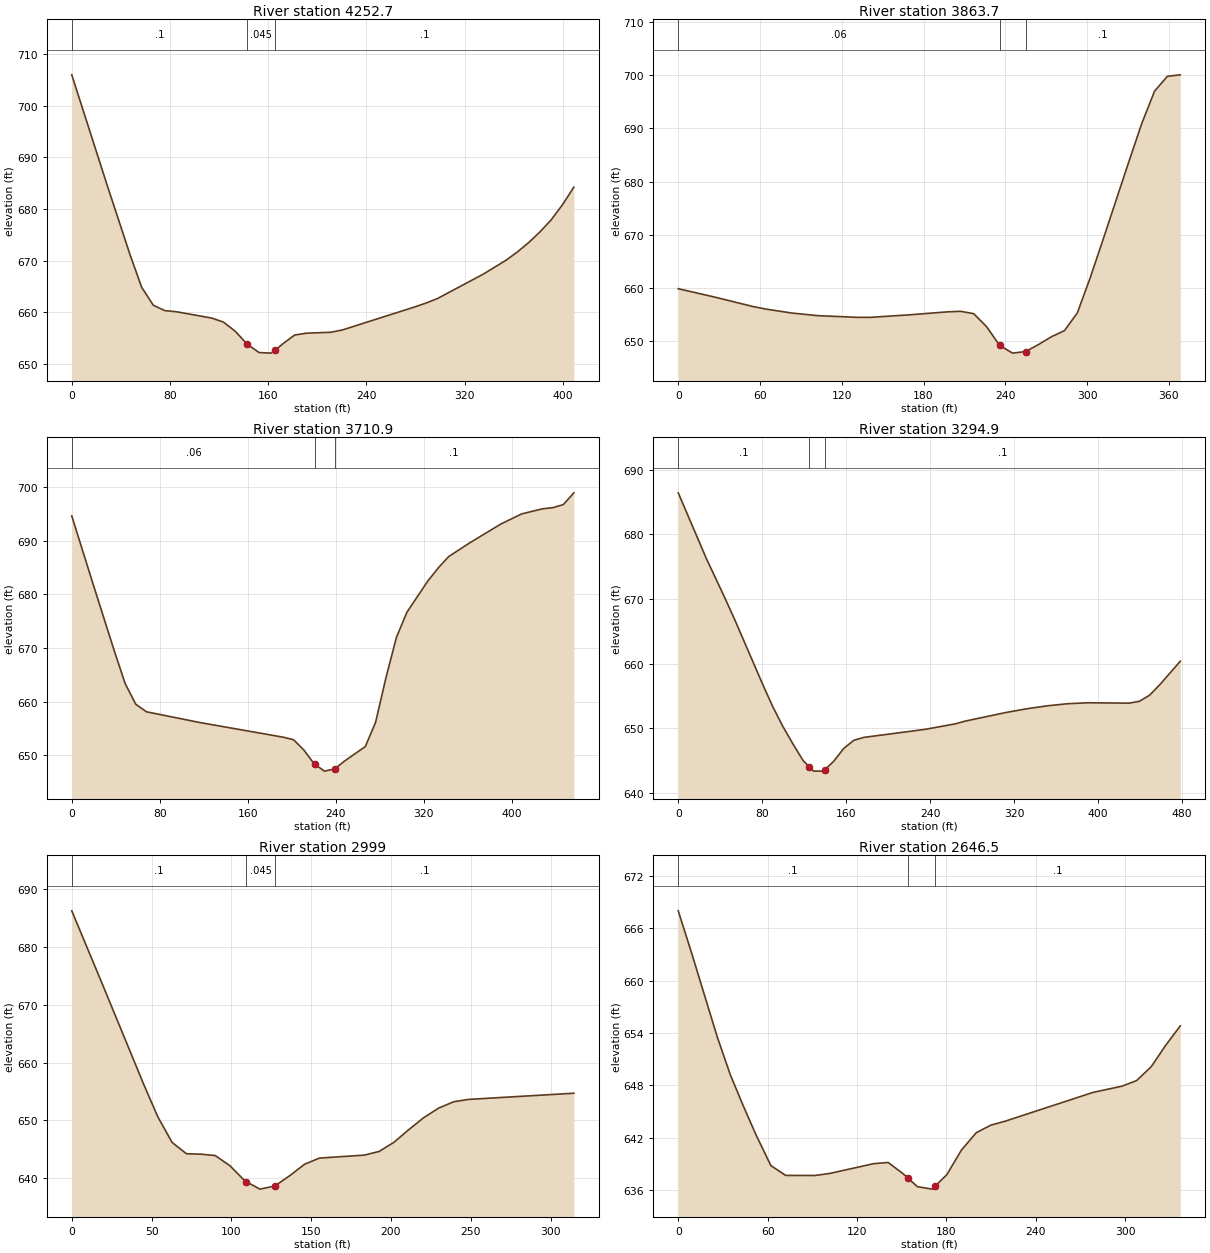
Type RM Length L Ch R = 1 ,4252.7  ,362.7,389,415.2
XS GIS Cut Line= 4
     1802272.099      443620.414     1802365.415      443685.518
     1802549.877      443625.839     1802646.448      443595.457
#Sta/Elev= 30
       0  705.95    28.4  684.91    47.4   671.2    56.9  664.88    66.4  661.38
    75.8  660.34    85.3  660.12   113.8  658.91   123.5  658.13   133.2  656.34
   142.9  653.83   152.6  652.23   162.2  652.12  165.63  652.68     172  653.94
   181.6  655.63   191.3  655.98   210.7  656.15   220.4   656.6   278.6     661
   288.3  661.78     298   662.7   335.3  667.42   353.7  670.09   362.9  671.69
   372.1   673.5   381.3  675.56   390.5  677.92   399.7  680.84   408.9  684.22
#Mann= 3 , 0 , 0
       0      .1       0   142.9    .045       0  165.63      .1       0
Bank Sta=142.9,165.63
XS Rating Curve= 0 ,0
Exp/Cntr=0.3,0.1

Type RM Length L Ch R = 1 ,3863.7  ,148.5,152.8,156.5
XS GIS Cut Line= 4
     1802246.058      443849.364     1802290.546      443896.021
     1802440.285      444068.548     1802489.113      444126.056
#Sta/Elev= 27
       0  659.88    27.6  658.25    55.3   656.5    64.5  656.04    83.5   655.3
   102.5  654.81   131.1   654.5   140.6  654.49   169.2  654.96   197.7  655.53
   207.2  655.63   216.8  655.19   226.3  652.73   235.8  649.23   245.3  647.77
   254.9  648.07   264.4  649.39   273.9  650.86   283.4     652   292.9  655.36
   302.3  661.95   311.8  669.18   330.6  683.72   340.1  690.92   349.5  697.01
   358.9   699.8   368.4  700.08
#Mann= 3 , 0 , 0
       0     .06       0   235.8    .045       0   254.9      .1       0
Bank Sta=235.8,254.9
XS Rating Curve= 0 ,0
Exp/Cntr=0.3,0.1

Type RM Length L Ch R = 1 ,3710.9  ,437.4,416.1,393.6
XS GIS Cut Line= 4
      1802128.87      443918.808     1802234.122       444032.74
     1802295.971      444136.907     1802397.967      444285.561
#Sta/Elev= 30
       0  694.58    19.4  681.89    38.8  669.38    48.5   663.4    58.2  659.54
    67.9  658.13   116.3  656.14   192.4   653.4   201.7  652.93     211  651.02
   220.3  648.47   221.1  648.35   229.7  647.09     239  647.49   248.3  649.01
   266.9  651.66   276.2  656.14   285.7   664.5   295.2  671.99   304.7  676.65
   323.7  682.46   333.2   684.9   342.7  687.02   361.6  689.54   390.1  693.07
   409.1  694.96   428.1  695.91   437.6  696.12     447   696.7   456.5  698.88
#Mann= 3 , 0 , 0
       0     .06       0   221.1    .045       0     239      .1       0
Bank Sta=221.1,239
XS Rating Curve= 0 ,0
Exp/Cntr=0.3,0.1

Type RM Length L Ch R = 1 ,3294.9  ,303.3,295.8,288.3
XS GIS Cut Line= 4
     1801813.115      444275.796     1801903.176      444280.136
     1802114.764      444297.497     1802288.375      444325.709
#Sta/Elev= 30
       0  686.45      27   676.2    45.1  669.94    54.1   666.7    81.2  656.51
    90.2  653.29    99.8  650.23   109.5   647.5   119.1  644.95   124.8  644.01
   128.8  643.35   138.4  643.34   139.8  643.56   148.1  644.86   157.7  646.86
   167.4  648.12     177  648.57   234.9   649.8   263.9  650.66   273.5  651.09
   312.2  652.42   331.8  652.99   351.3  653.45   370.9  653.78   390.4  653.93
   429.5  653.87   439.3  654.15     449  655.08   458.8  656.72   478.4  660.37
#Mann= 3 , 0 , 0
       0      .1       0   124.8    .045       0   139.8      .1       0
Bank Sta=124.8,139.8
XS Rating Curve= 0 ,0
Exp/Cntr=0.3,0.1

Type RM Length L Ch R = 1 ,2999    ,347.8,352.6,357.1
XS GIS Cut Line= 4
     1801902.091      444606.742     1801984.556      444570.935
      1802120.19      444536.212      1802203.74      444522.107
#Sta/Elev= 25
       0  686.29      18  674.37      45  656.27    53.9   650.6    62.9  646.14
    71.9  644.19    80.9  644.12    89.9  643.88    99.2  642.09   108.6  639.45
   109.4  639.33   117.9  638.06   127.2   638.6   136.6  640.39   145.9  642.38
   155.2  643.44   183.2  643.95   192.6  644.59   201.9  646.18   211.2  648.37
   220.6  650.46   229.9   652.1   239.3   653.2   248.7  653.61   314.6  654.68
#Mann= 3 , 0 , 0
       0      .1       0   109.4    .045       0   127.2      .1       0
Bank Sta=109.4,127.2
XS Rating Curve= 0 ,0
Exp/Cntr=0.3,0.1

Type RM Length L Ch R = 1 ,2646.5  ,313.6,319.7,326.6
XS GIS Cut Line= 4
      1801974.79      444883.435     1802025.789       444895.37
     1802192.889      444887.775     1802290.546      444822.671
#Sta/Elev= 28
       0  667.98     8.7  663.31    26.2  653.55    34.9  649.25    43.6  645.69
    52.4  642.28    62.2  638.83    72.1  637.71    91.7   637.7   101.6  637.93
   131.1  639.05   140.9  639.19   150.8  637.92   154.3  637.38   160.6  636.42
   170.4  636.14  172.36  636.47   180.3   637.8   190.1  640.61     200  642.59
   209.8  643.46   219.6  643.92   278.3   647.2   297.9  647.92   307.7  648.56
   317.5  650.15   327.2   652.6     337  654.82
#Mann= 3 , 0 , 0
       0      .1       0   154.3    .045       0  172.36      .1       0
Bank Sta=154.3,172.36
XS Rating Curve= 0 ,0
Exp/Cntr=0.3,0.1

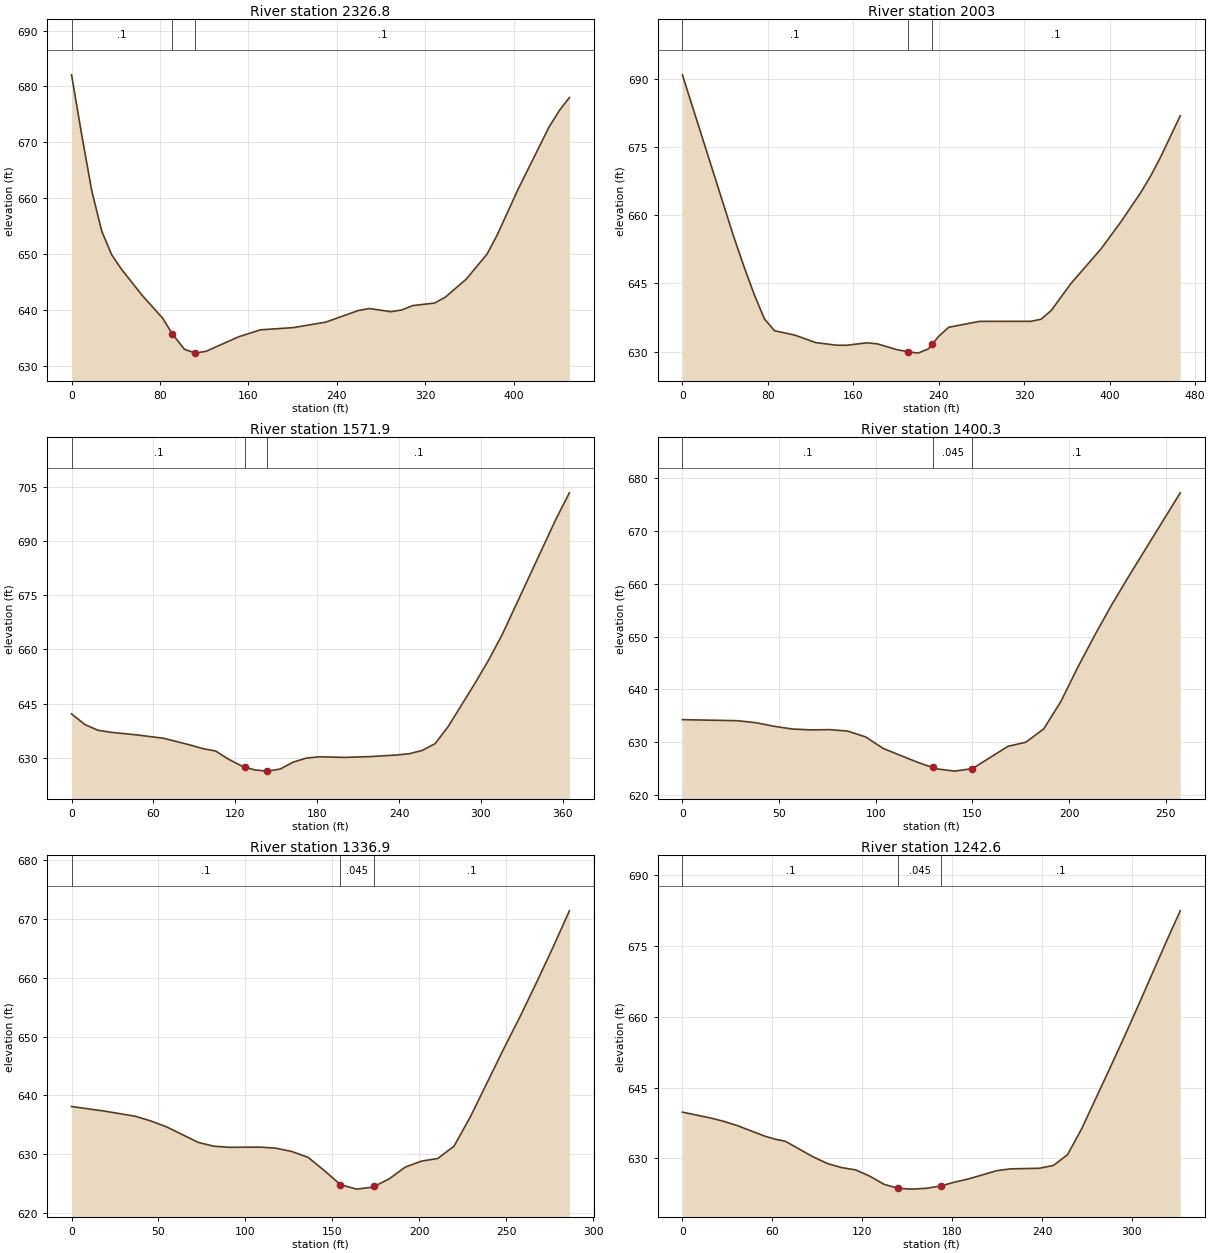
Type RM Length L Ch R = 1 ,2326.8  ,322.8,323.7,324.6
XS GIS Cut Line= 4
     1801971.535      445108.044     1802044.235      445109.129
     1802312.247      445172.063     1802391.457      445237.167
#Sta/Elev= 30
       0  682.08     9.1  671.47    18.2  661.42    27.3  654.12    36.4  649.86
    45.4  647.25    63.6  642.71    82.5  638.53    91.1  635.76   102.2  632.98
     112   632.3   121.9  632.64   151.4  635.24     171  636.47   200.5  636.86
     230  637.84   259.5  639.92   269.4  640.28     289  639.71   298.8  640.02
   308.7   640.8   328.4  641.25   338.2   642.3   357.3  645.56     376  650.02
   385.3  653.48   403.9  661.54   431.9  672.67   441.2  675.63   450.5  678.02
#Mann= 3 , 0 , 0
       0      .1       0    91.1    .045       0     112      .1       0
Bank Sta=91.1,112
XS Rating Curve= 0 ,0
Exp/Cntr=0.3,0.1

Type RM Length L Ch R = 1 ,2003    ,425.2,431.1,436.1
XS GIS Cut Line= 3
     1801932.473      445345.674     1802263.419      445444.416
     1802383.862      445453.096
#Sta/Elev= 30
       0  690.85      48   655.3    57.6  648.74    67.2   642.6    76.8   637.2
    86.3  634.61   105.5  633.63   124.7  632.01   143.9  631.44   153.5  631.41
   172.7  631.95   182.3  631.74   201.5  630.41     211  630.02   220.6  629.69
   230.2  630.61   233.9  631.67   239.8  633.35   249.4  635.38   278.2  636.67
   326.2  636.68   335.8  637.14   345.4  639.08   363.9  645.03   391.8  652.56
   410.4  658.49     429  664.93   438.2  668.53   447.5  672.67   466.1  681.85
#Mann= 3 , 0 , 0
       0      .1       0     211    .045       0   233.9      .1       0
Bank Sta=211,233.9
XS Rating Curve= 0 ,0
Exp/Cntr=0.3,0.1

Type RM Length L Ch R = 1 ,1571.9  ,170.4,171.6,172.9
XS GIS Cut Line= 4
      1801891.24      445647.324     1801940.068      445718.938
     1802097.403      445805.744     1802152.742      445887.124
#Sta/Elev= 30
       0   642.2     9.6  639.27    19.3  637.66    28.9   637.1    48.2  636.36
    67.4  635.45    86.7  633.61    96.1   632.6   105.6  631.92     115  629.67
   124.5  627.83   127.2  627.51     134  626.71   143.4  626.37   152.9  626.94
   162.3  628.84   171.8  629.94   181.2  630.33   200.2  630.16   219.1  630.39
     238  630.82   247.4  631.17   256.9  632.08   266.4  633.95   276.2   638.8
   295.9  650.82   305.7  657.11   315.6  664.11   354.9  695.94   364.8  703.26
#Mann= 3 , 0 , 0
       0      .1       0   127.2    .045       0   143.4      .1       0
Bank Sta=127.2,143.4
XS Rating Curve= 0 ,0
Exp/Cntr=0.3,0.1

Type RM Length L Ch R = 1 ,1400.3  ,68,63.4,58.7
XS GIS Cut Line= 4
     1801838.072      445808.999      1801893.41      445874.103
     1801976.961      445931.612     1802025.789       445982.61
#Sta/Elev= 24
       0  634.26    28.5  634.06      38  633.68    47.5     633      57  632.48
    66.5  632.32      76  632.37    85.4   632.1    94.7     631   103.9   628.8
   122.3  626.09   129.4  625.21   131.6  624.94   140.8  624.51     150  624.98
   168.4  629.21   177.6  629.98   186.9  632.51   195.7  637.66   204.5  644.17
   213.4  650.33   222.2   656.1     231  661.48   257.5  677.22
#Mann= 3 , 0 , 0
       0      .1       0   129.4    .045       0     150      .1       0
Bank Sta=129.4,150
XS Rating Curve= 0 ,0
Exp/Cntr=0.3,0.1

Type RM Length L Ch R = 1 ,1336.9  ,88.7,94.3,99.8
XS GIS Cut Line= 5
     1801751.266      445892.549      1801809.86      445935.952
     1801854.348      445935.952     1801948.749        445976.1
     1802000.832      446017.332
#Sta/Elev= 28
       0  638.09    18.2  637.35    36.5  636.45    45.6  635.64    54.7  634.63
    72.9  631.99    81.8  631.35    90.7  631.16   108.5  631.19   117.4  631.02
   126.7  630.45   136.1  629.45   145.4  627.21   154.7  624.81     164  624.05
   173.4   624.4   174.2  624.52   182.7  625.79     192   627.8   201.3  628.81
   210.7  629.26     220  631.34   229.5  636.38   248.5  647.84     258  653.37
   267.4  659.12   276.9  665.11   286.4  671.37
#Mann= 3 , 0 , 0
       0      .1       0   154.7    .045       0   174.2      .1       0
Bank Sta=154.7,174.2
XS Rating Curve= 0 ,0
Exp/Cntr=0.3,0.1

Type RM Length L Ch R = 1 ,1242.6  ,73,68.7,64.7
XS GIS Cut Line= 5
     1801702.438      445953.313     1801755.606      445967.419
     1801767.542      445973.929     1801918.367      446086.777
     1801991.066      446106.308
#Sta/Elev= 30
       0  639.82    18.3  638.61    27.5  637.88    36.7  636.96      55  634.73
    61.8  634.09    68.6  633.66    87.4  630.31    96.9  628.91   106.3  628.06
   115.7  627.57   125.1  626.23   134.5  624.53     144  623.66   153.4   623.5
   162.8  623.67   172.7  624.19   181.6  624.98     191  625.67   209.9  627.42
   219.3   627.8   238.1  627.92   247.6  628.52     257  630.81   266.4  636.27
   285.2  649.09   294.6  655.59     304  662.27   322.8  675.89   332.2  682.49
#Mann= 3 , 0 , 0
       0      .1       0     144    .045       0   172.7      .1       0
Bank Sta=144,172.7
XS Rating Curve= 0 ,0
Exp/Cntr=0.3,0.1

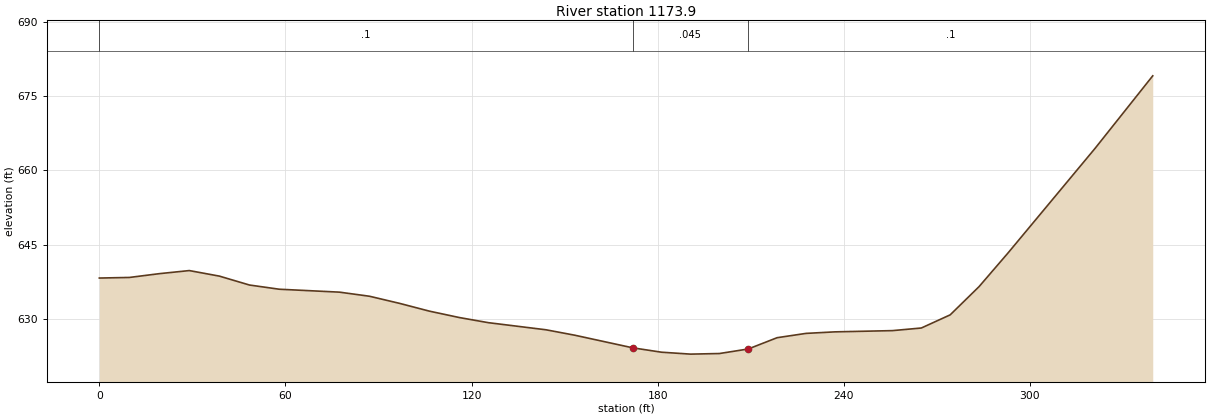
Type RM Length L Ch R = 1 ,1173.9  ,533.6,528.7,519.6
XS GIS Cut Line= 4
      1801651.44      446068.331     1801767.542      446068.331
     1801909.686      446137.775     1801973.705      446150.796
#Sta/Elev= 30
       0  638.25     9.7  638.37    19.4  639.14      29  639.76    38.7  638.64
    48.4  636.84      58  635.99    77.4   635.4    87.1  634.57    96.8  633.13
   106.4  631.56   116.1  630.26   125.4  629.23     144  627.79   153.3  626.69
   171.9  624.15   181.2  623.26   190.6  622.87   199.9  622.99   209.2  623.91
   218.5  626.19   227.8  627.06   237.1  627.37   255.7  627.62     265  628.15
   274.3  630.81   283.6  636.51     293  643.36     321  664.46   339.6  679.13
#Mann= 3 , 0 , 0
       0      .1       0   171.9    .045       0   209.2      .1       0
Bank Sta=171.9,209.2
XS Rating Curve= 0 ,0
Exp/Cntr=0.3,0.1