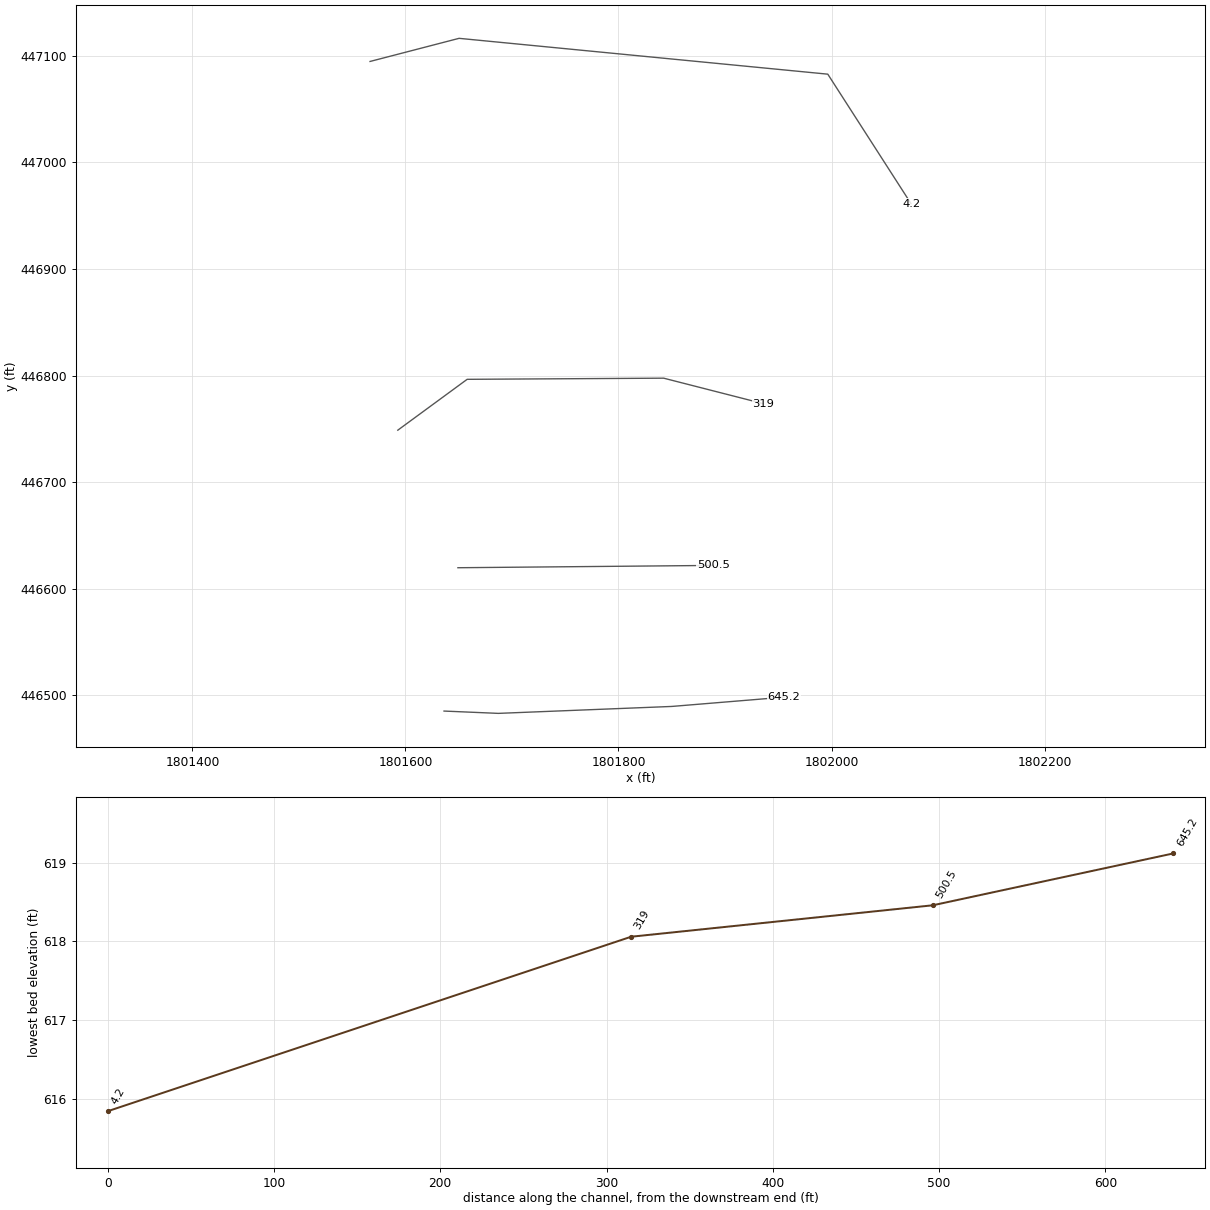
HEC-RAS study LEFTFORK2.prj: LEFTFORK2

--- LEFTFORK2.g01 (geometry) --- (continued)

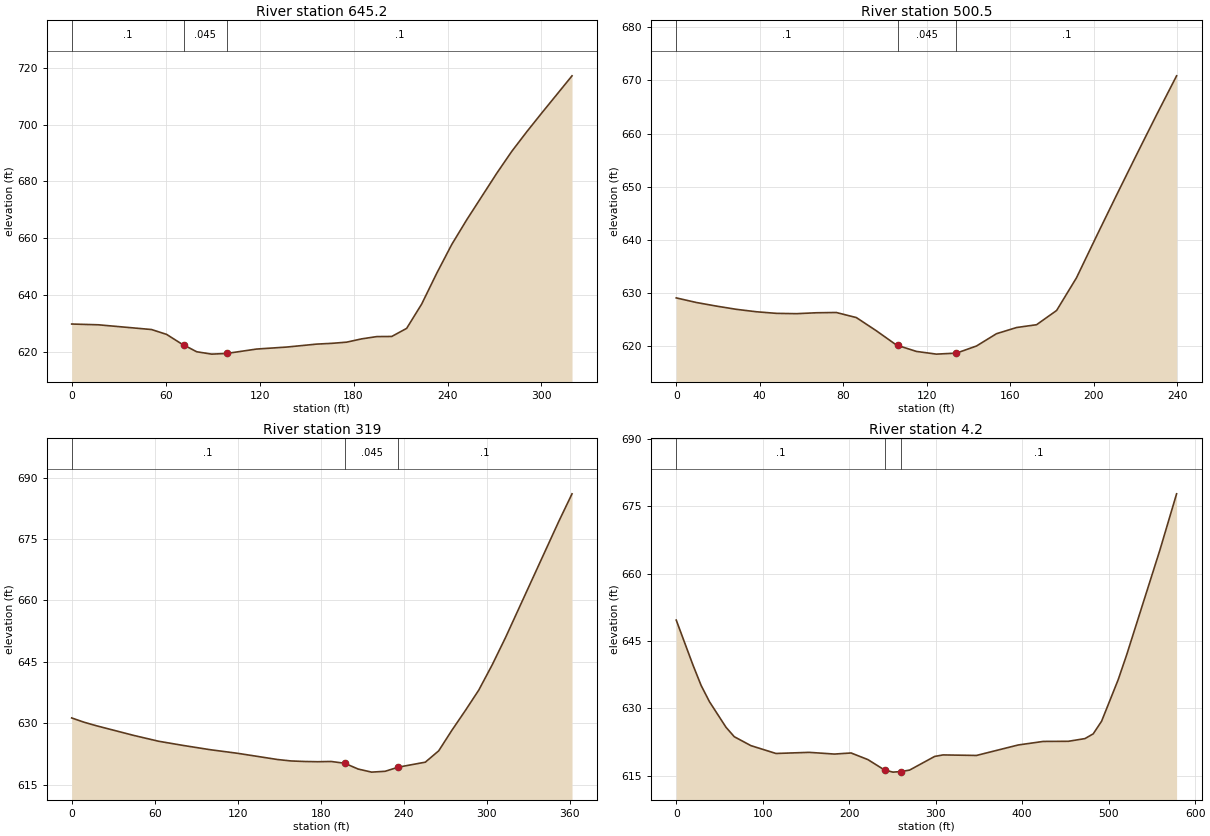
Type RM Length L Ch R = 1 ,645.2   ,145.6,144.7,144
XS GIS Cut Line= 4
     1801636.249      446484.997     1801687.247      446482.827
     1801850.007      446489.337     1801955.259      446498.018
#Sta/Elev= 27
       0  629.73      17  629.46      51  627.79    60.6  626.08    70.2  622.73
    71.6  622.33    79.8  619.96    89.4  619.12      99  619.36   118.1  620.91
   137.3  621.61   156.4  622.65     166  622.92   175.6  623.34   185.2   624.5
   194.8   625.3   204.4  625.35   213.9   628.2   223.5  636.78   233.1  647.62
   242.7  657.78   252.3  666.51   271.5  682.93   281.1  690.66   290.7  697.58
   300.3  704.21   319.5  717.23
#Mann= 3 , 0 , 0
       0      .1       0    71.6    .045       0      99      .1       0
Bank Sta=71.6,99
XS Rating Curve= 0 ,0
Exp/Cntr=0.3,0.1

Type RM Length L Ch R = 1 ,500.5   ,180.8,181.4,181.1
XS GIS Cut Line= 2
      1801649.27      446619.546      1801889.07      446621.716
#Sta/Elev= 28
       0  629.05     9.6  628.19    19.2  627.51    28.8   626.9    38.4  626.44
      48  626.14    57.6  626.08    67.2  626.25    76.7   626.3    86.3  625.35
    95.9  622.86   105.5  620.18   106.1   620.1   115.1  618.97   121.1  618.65
   124.7  618.46   134.3  618.65   143.9  619.99   153.5  622.31   163.1  623.47
   172.7     624   182.3  626.68   191.8  632.82   201.4  640.66     211  648.39
   220.6  656.01   230.2  663.53   239.8  670.88
#Mann= 3 , 0 , 0
       0      .1       0   106.1    .045       0   134.3      .1       0
Bank Sta=106.1,134.3
XS Rating Curve= 0 ,0
Exp/Cntr=0.3,0.1

Type RM Length L Ch R = 1 ,319     ,317.9,314.8,311.7
XS GIS Cut Line= 4
     1801592.846      446748.669      1801657.95      446796.412
     1801842.412      446797.497     1801935.728      446773.626
#Sta/Elev= 27
       0  631.29       9  630.24    17.9  629.38    44.8  627.03    62.8   625.6
    80.7  624.57   100.2  623.53   119.6  622.67   148.7  621.14   158.4  620.79
   168.1  620.66   177.8   620.6   187.5  620.66   197.2  620.23     207  618.81
   216.7  618.06   226.4  618.26   236.1  619.28   255.5  620.49   265.2  623.27
   274.8  628.33   284.5  633.14   294.1  638.08   303.7  644.18   313.4  650.89
   351.9  679.26   361.5  686.02
#Mann= 3 , 0 , 0
       0      .1       0   197.2    .045       0   236.1      .1       0
Bank Sta=197.2,236.1
XS Rating Curve= 0 ,0
Exp/Cntr=0.3,0.1

Type RM Length L Ch R = 1 ,4.2     ,5.3,4.2,3.2
XS GIS Cut Line= 4
     1801566.804      447094.806     1801650.355      447116.508
     1801996.492       447082.87     1802074.617      446961.343
#Sta/Elev= 30
       0  649.67    19.2  639.74    28.8  635.12    38.4  631.52      48  628.66
    57.6  625.81    67.1  623.72    86.3  621.74   115.3  619.99   153.9  620.24
   182.9  619.86   202.2   620.1   221.6  618.63   240.9  616.31   250.6  615.84
   260.2  615.97   269.9   616.3   298.8  619.33   308.5  619.67   347.2  619.55
   395.4  621.88   424.4  622.67   453.4   622.7   472.6   623.3   482.2  624.36
   491.9  627.18   511.1  636.43   520.8   641.9   559.3  665.26   578.6  677.77
#Mann= 3 , 0 , 0
       0      .1       0   240.9    .045       0   260.2      .1       0
Bank Sta=240.9,260.2
XS Rating Curve= 0 ,0
Exp/Cntr=0.3,0.1

Chan Stop Cuts=-1
Use User Specified Reach Order=0
Composite Channel Slope=5